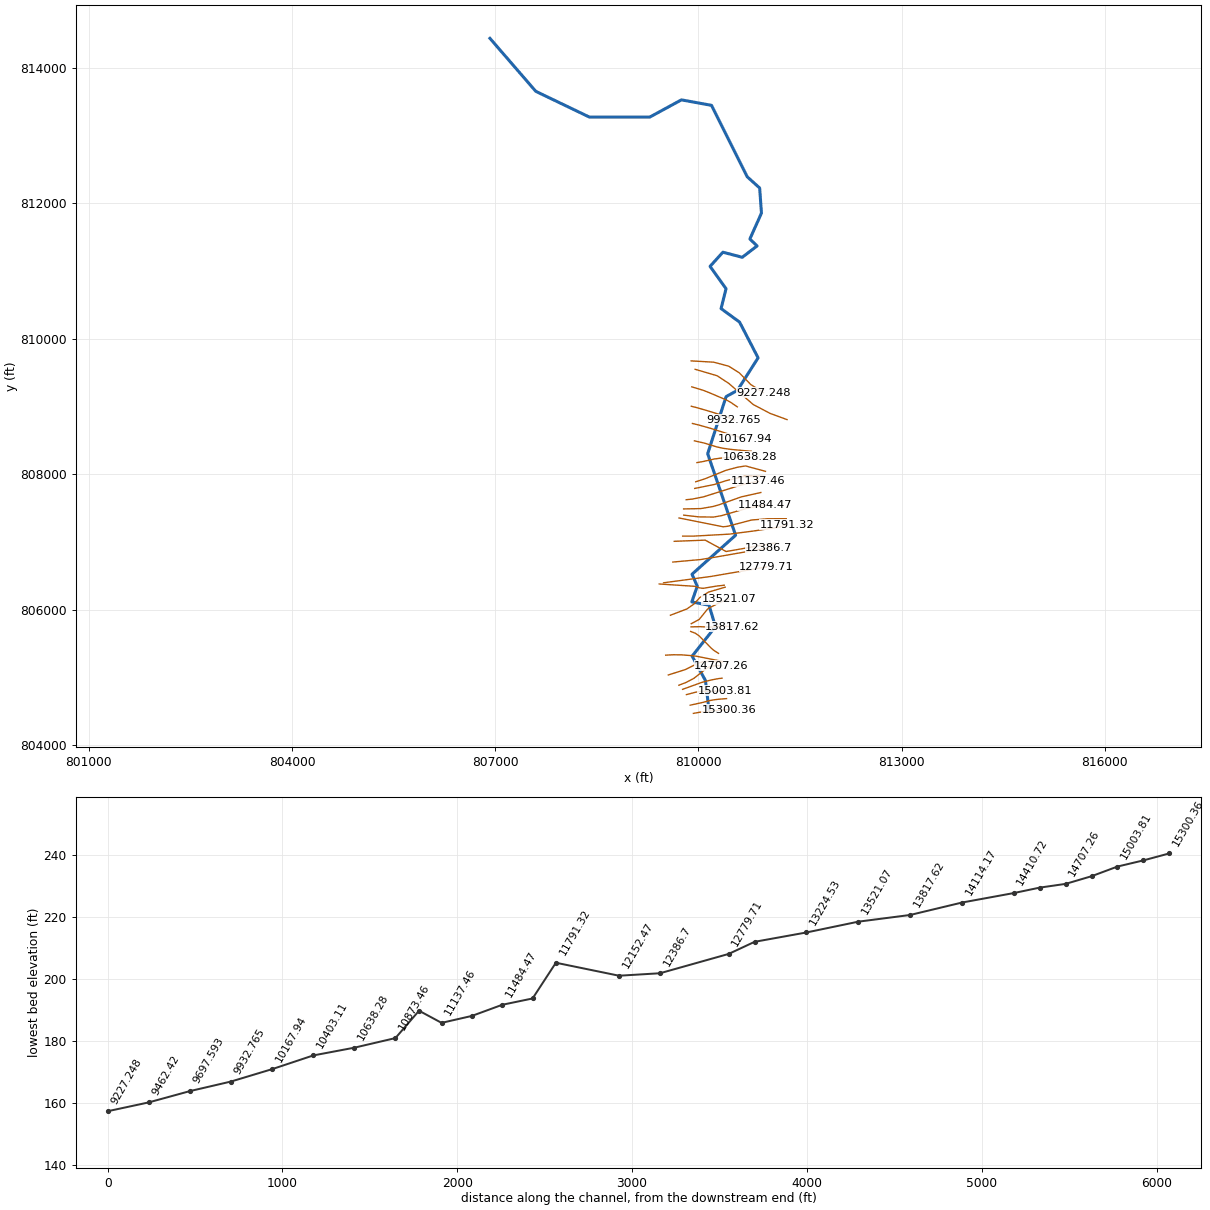
--- 18137_ras.prj (project) ---

Proj Title=18137
Current Plan=p01
Default Exp/Contr=0.3,0.1
English Units
Geom File=g01
Flow File=f01
Plan File=p01
Y Axis Title=Elevation
X Axis Title(PF)=Main Channel Distance
X Axis Title(XS)=Station
BEGIN DESCRIPTION:
RFD model 18137 exported to HEC-RAS
END DESCRIPTION:

--- 18137_ras.p01 (plan) ---

Plan Title=Plan 01
Program Version=4.10
Short Identifier=Plan 01
Geom File=g01
Flow File=f01
Subcritical Flow
Calc Critical at every XS
Secant Critical Depth

--- 18137_ras.f01 (steady flow) ---

Flow Title=Flow 01
Program Version=5.01
Number of Profiles= 6
Profile Names=10yr,25yr,50yr,100yr,100plus,500yr
River Rch & RM=18137,42,15300.36
  862.34 1404.32 1920.48 2397.53 3500.39 4898.73
River Rch & RM=18137,42,15152.09
  863.87 1406.87 1924.03 2402.01 3506.94 4906.85
River Rch & RM=18137,42,15003.81
  865.15    1409 1926.99 2405.76  3512.4 4913.61
River Rch & RM=18137,42,14855.54
  866.43 1411.14 1929.96  2409.5 3517.87 4920.37
River Rch & RM=18137,42,14707.26
  875.56 1426.37 1951.14  2436.3    3557 4968.93
River Rch & RM=18137,42,14558.99
  895.19 1459.41 1997.32 2495.01 3642.72 5076.18
River Rch & RM=18137,42,14410.72
  900.97 1469.19 2011.02 2512.47  3668.2 5108.18
River Rch & RM=18137,42,14114.17
  905.09 1476.13 2020.74 2524.84 3686.27 5130.81
River Rch & RM=18137,42,13817.62
  912.13    1488 2037.34 2545.96  3717.1  5169.3
River Rch & RM=18137,42,13521.07
  917.95  1497.8 2051.06 2563.41 3742.58 5201.08
River Rch & RM=18137,42,13224.53
  921.79 1504.29 2060.15 2574.99 3759.49 5222.22
River Rch & RM=18137,42,12927.98
  941.78 1538.24 2107.86 2635.93 3848.46 5333.97
River Rch & RM=18137,42,12779.71
  942.73 1539.85 2110.11 2638.81 3852.66 5339.21
River Rch & RM=18137,42, 12386.7
  945.95 1545.34 2117.87 2648.74 3867.16 5357.52
River Rch & RM=18137,42,12152.47
  947.78 1548.46 2122.27 2654.39 3875.42 5367.97
River Rch & RM=18137,42,11791.32
  968.87 1584.14 2172.28 2718.14 3968.48 5483.73
River Rch & RM=18137,42,11657.98
 1021.62 1672.82  2296.2 2875.59 4198.36 5765.84
River Rch & RM=18137,42,11484.47
 1028.34 1684.32 2312.45 2896.43 4228.79 5803.89
River Rch & RM=18137,42,11310.96
 1031.92 1690.45  2321.1 2907.53    4245 5824.14
River Rch & RM=18137,42,11137.46
 1033.27 1692.75 2324.34  2911.7 4251.08 5831.73
River Rch & RM=18137,42,11008.48
 1037.74  1700.4 2335.15 2925.56 4271.31 5856.99
River Rch & RM=18137,42,10873.46
 1039.75 1703.84 2340.01 2931.79 4280.42 5868.35
River Rch & RM=18137,42,10638.28
 1044.57 1712.13 2351.76 2946.91 4302.49 5896.07
River Rch & RM=18137,42,10403.11
 1047.33 1716.92 2358.59 2955.74 4315.38 5912.42
River Rch & RM=18137,42,10167.94
 1054.54 1729.44 2376.42 2978.79 4349.04 5955.12
River Rch & RM=18137,42,9932.765
 1057.29 1734.22 2383.24  2987.6 4361.89 5971.41
River Rch & RM=18137,42,9697.593
 1058.77 1736.79  2386.9 2992.34 4368.81 5980.17
River Rch & RM=18137,42, 9462.42
 1550.52  2549.2 3509.75 4404.66  6430.8 8350.91
River Rch & RM=18137,42,9227.248
 1552.67 2552.93 3515.08 4411.54 6440.85 8362.99
River Rch & RM=18137,42,8992.075
 1554.42 2555.98 3519.43 4417.17 6449.07 8372.86
River Rch & RM=18137,42,8756.903
 1556.86 2560.27  3525.6  4425.2  6460.8 8387.11
River Rch & RM=18137,42, 8521.73
 1560.99 2567.53 3536.03 4438.77  6480.6 8411.21
River Rch & RM=18137,42,    8376
 1563.42 2571.81 3542.18 4446.78  6492.3 8425.44
River Rch & RM=18137,42,  7548.5
  1577.7 2596.91 3578.21 4493.64 6560.72 8508.44
River Rch & RM=18137,42, 7075.68
 1715.57 2835.38  3917.5 4931.45 7199.92 9263.89
River Rch & RM=18137,42,6130.041
 1744.55 2886.38 3990.84 5026.95 7339.35 9430.91
River Rch & RM=18137,42,5818.041
 1748.14 2892.72 3999.97 5038.87 7356.75 9451.83
River Rch & RM=18137,42,5563.235
  1756.2 2906.97 4020.52 5065.68 7395.89 9498.85
River Rch & RM=18137,42,5159.309
 1757.99 2910.13 4025.07 5071.63 7404.58 9509.29
Boundary for River Rch & Prof#=18137,42,1
Up Type= 0
Dn Type= 2
Boundary for River Rch & Prof#=18137,42,2
Up Type= 0
Dn Type= 2
Boundary for River Rch & Prof#=18137,42,2
Up Type= 0
Dn Type= 2
Boundary for River Rch & Prof#=18137,42,2
Up Type= 0
Dn Type= 2
Boundary for River Rch & Prof#=18137,42,2
Up Type= 0
Dn Type= 2
Boundary for River Rch & Prof#=18137,42,2
Up Type= 0
Dn Type= 2

--- 18137_ras.g01 (geometry) ---

Geom Title=18137
Program Version=4.10

River Reach=18137,42
Reach XY= 30
810157.508590728804500.378989796810103.632993966804951.607636947
809906.585841657805312.052529944810251.262821588805748.425866406
810155.474999401 806064.20191368809901.870994839806113.058872482
809982.532184155806344.490257394809904.655354679806520.999230166
810548.405774833807096.889163428 810136.09859446808300.455610153
810407.918295624809143.268588822810574.356429878809234.311221802
810880.312155578  809715.6903049 810606.73814115810243.383962555
810333.883784175810442.545880117 810407.11480835810736.216188987
810171.430325897811065.736515984810360.580075591 811274.91991146
810646.840817512811199.802205702810865.469878017811367.631204811
810758.984898778811469.765582067810930.033032598811852.084143329
810903.521962704812222.504524268810719.928212732812387.869107569
810192.584462704813442.556607564809748.792218836813523.697697689
809281.126129392813269.379524253 808390.50112936813269.379524253
807598.834462702 813649.58785757806921.909271152814431.935822634

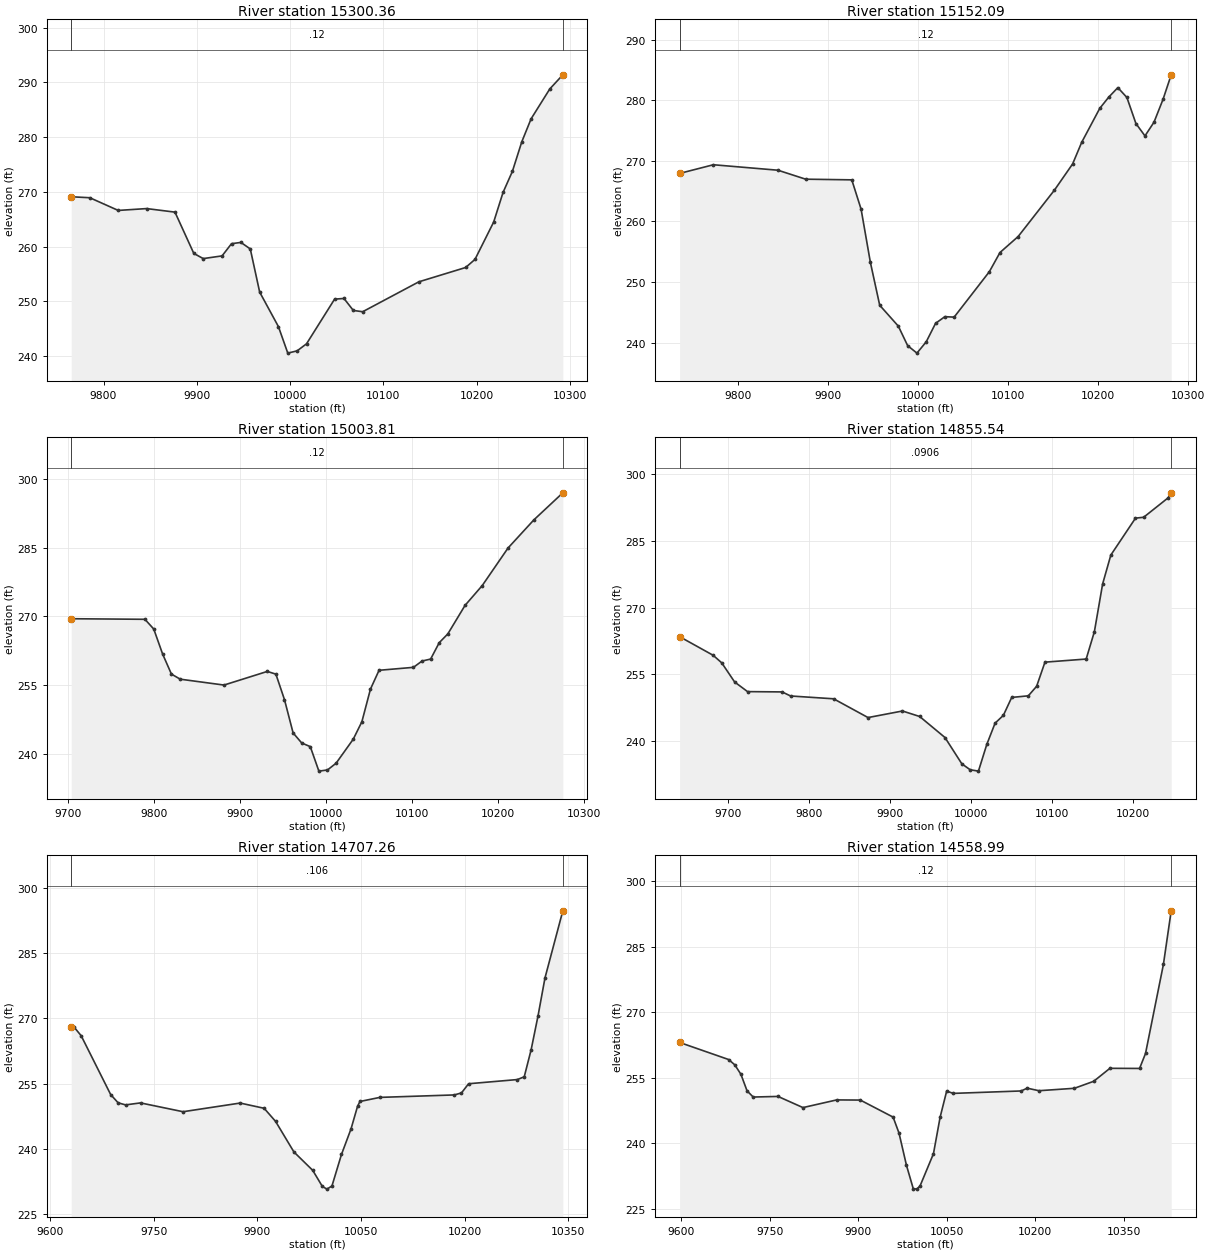
Type RM Length L Ch R = 1 ,15300.36,148.273800,148.273800,148.273800
XS GIS Cut Line= 6
809925.400648096804467.333527562810017.659908186804483.698830034
810102.770393035804495.765661501810285.124088927804512.540279454
810405.189590231804521.662102162810448.963021761804523.825834161
#Sta/Elev= 30
  9765.4269.09679785.306268.91829815.774266.59659846.242266.93489876.613266.2862
9896.813258.73229906.913 257.7929927.113258.28419937.213260.51359947.303 260.748
9957.356259.55519967.408 251.6669987.514245.35539997.567240.504410007.61240.9226
10017.65242.208510047.76250.3809 10057.8250.496810067.84248.304910077.87 248.075
10138.09253.544710188.24256.161610198.27257.646610218.32264.482810228.35269.8882
10238.38273.744810248.41279.134510258.42283.349110278.45288.808610292.43 291.392
#Mann= 3 , 0 , 0
  9765.4    0.12       0  9765.4    0.12       010292.43    0.12       0
#XS Ineff= 2 , 0
       0                               0
Bank Sta=9765.4,10292.43
Exp/Cntr=0.3,0.1

Type RM Length L Ch R = 1 ,15152.09,148.273700,148.273700,148.273700
XS GIS Cut Line= 6
809878.416009688804588.409326598810065.487953862804629.540987788
810172.598363016804657.196961228810221.729018818804666.592106238
810303.496785057804676.824755195810414.024717093804685.352199201
#Sta/Elev= 30
9735.673267.93189773.131269.36539844.803268.4616 9875.52266.98169926.714266.8715
9937.037262.02579947.364253.21959957.692246.15679978.346 242.7079988.673239.4901
    9999238.248610009.34240.126110019.67243.168910029.99244.270710040.28244.1946
10079.38251.706710091.16254.870410111.31  257.5110151.62265.184310171.77269.5071
 10181.8273.066410201.87278.6832 10211.9280.547110221.93282.103210231.96280.4807
10241.99276.171110252.03274.128210262.06276.402810272.09280.177710281.12284.2189
#Mann= 3 , 0 , 0
9735.673    0.12       09735.673    0.12       010281.12    0.12       0
#XS Ineff= 2 , 0
       0                               0
Bank Sta=9735.673,10281.12
Exp/Cntr=0.3,0.1

Type RM Length L Ch R = 1 ,15003.81,148.273800,148.273800,148.273800
XS GIS Cut Line= 6
 809822.36261632804744.238993038809959.477723631804780.412146581
810016.957090357804790.306184622810075.497069386804794.383521047
810193.225986532804791.383229095810388.669512552804802.574086846
#Sta/Elev= 30
9703.324269.4817 9789.11269.35789799.399267.23679809.688261.80349819.976 257.414
9830.265256.30179881.205255.02139931.596257.9922 9941.62257.40439951.644251.8265
9961.668244.58639971.675242.39539981.681241.59589991.687236.2589 10001.7236.5123
10011.71237.982510031.74243.234610041.74247.022210051.74 254.13810061.74258.2408
10101.78 258.88410111.79260.257810121.81260.689310131.83264.262510141.84266.1764
10161.87272.388810181.91276.715210211.96284.904310242.01291.029710275.73 296.929
#Mann= 3 , 0 , 0
9703.324    0.12       09703.324    0.12       010275.73    0.12       0
#XS Ineff= 2 , 0
       0                               0
Bank Sta=9703.324,10275.73
Exp/Cntr=0.3,0.1

Type RM Length L Ch R = 1 ,14855.54,148.273700,148.273700,148.273700
XS GIS Cut Line= 6
809765.822412081804822.442999427810048.092870519804924.140466302
810093.793935906804937.409291832 810208.52082909804964.589715738
 810305.74871143804982.145616114810348.909117466804986.393884392
#Sta/Elev= 30
9639.634263.44029681.072259.2472 9691.71257.54119707.651253.22589723.624251.0581
9766.286250.99219776.813250.07559830.003249.44099872.555245.21239915.107246.6917
9936.383245.45329967.691240.71149988.501234.78969998.782233.452410009.05233.1405
10019.33239.142310029.61243.948410039.88245.716510050.16 249.74910070.72250.1136
10080.99252.262610091.27257.699510142.23258.400110152.39264.576110162.56275.3233
10172.72281.8367 10203.2290.154810213.26290.346710243.41294.711510247.33295.8584
#Mann= 3 , 0 , 0
9639.634  0.0906       09639.634  0.0906       010247.33  0.0906       0
#XS Ineff= 2 , 0
       09924.614                       0
Bank Sta=9639.634,10247.33
Exp/Cntr=0.3,0.1

Type RM Length L Ch R = 1 ,14707.26,148.273800,148.273800,148.273800
XS GIS Cut Line= 6
809711.446348416804882.945943504809816.851450452804923.845568462
809931.565371159804983.868633854810131.360195384805140.915055541
810225.036017843805168.924526434810340.831835074805172.844378702
#Sta/Elev= 30
9630.397267.96589634.166268.06889644.773266.01529687.509252.45489698.305250.5499
9709.101250.07659730.692250.53499792.282248.50239875.019250.4985 9909.72249.2924
9926.319 246.2719952.823239.23589980.095234.99049994.033231.289610000.69230.6616
10007.95231.392610021.74238.658610035.54244.535410044.95 249.72210048.44250.8604
10077.31251.805310185.19252.370510195.52252.839810205.85254.9507 10276.4255.9126
 10286.4256.552210296.41262.799210306.41270.626210316.42279.324210342.27294.8026
#Mann= 3 , 0 , 0
9630.397   0.106       09630.397   0.106       010342.27   0.106       0
#XS Ineff= 2 , 0
       0                               0
Bank Sta=9630.397,10342.27
Exp/Cntr=0.3,0.1

Type RM Length L Ch R = 1 ,14558.99,148.273800,148.273800,148.273800
XS GIS Cut Line= 6
 809554.83526324805034.346503097809804.276375156805113.201884902
809995.668119217805208.108762095810073.881684447805232.495685397
810217.682923556805236.411033903810348.069791237805220.529736918
#Sta/Elev= 30
9597.184263.03789680.201259.13119690.629257.92239701.056255.75829711.483251.9582
 9721.91250.53969763.961250.67889806.273248.12449863.485 249.8829903.484249.8449
9959.059245.94329969.057242.28949981.704234.9076 9993.14229.5876    9999229.4526
10004.64230.152310027.46237.562310038.75245.921410049.85 251.90410060.94251.3757
10176.17251.932110186.27252.568710206.31251.987910266.37252.543510299.07254.1434
10326.55 257.11710376.85257.086710386.92260.515510417.24 280.90710430.44293.1795
#Mann= 3 , 0 , 0
9597.184    0.12       09597.184    0.12       010430.44    0.12       0
#XS Ineff= 2 , 0
       0                               0
Bank Sta=9597.184,10430.44
Exp/Cntr=0.3,0.1

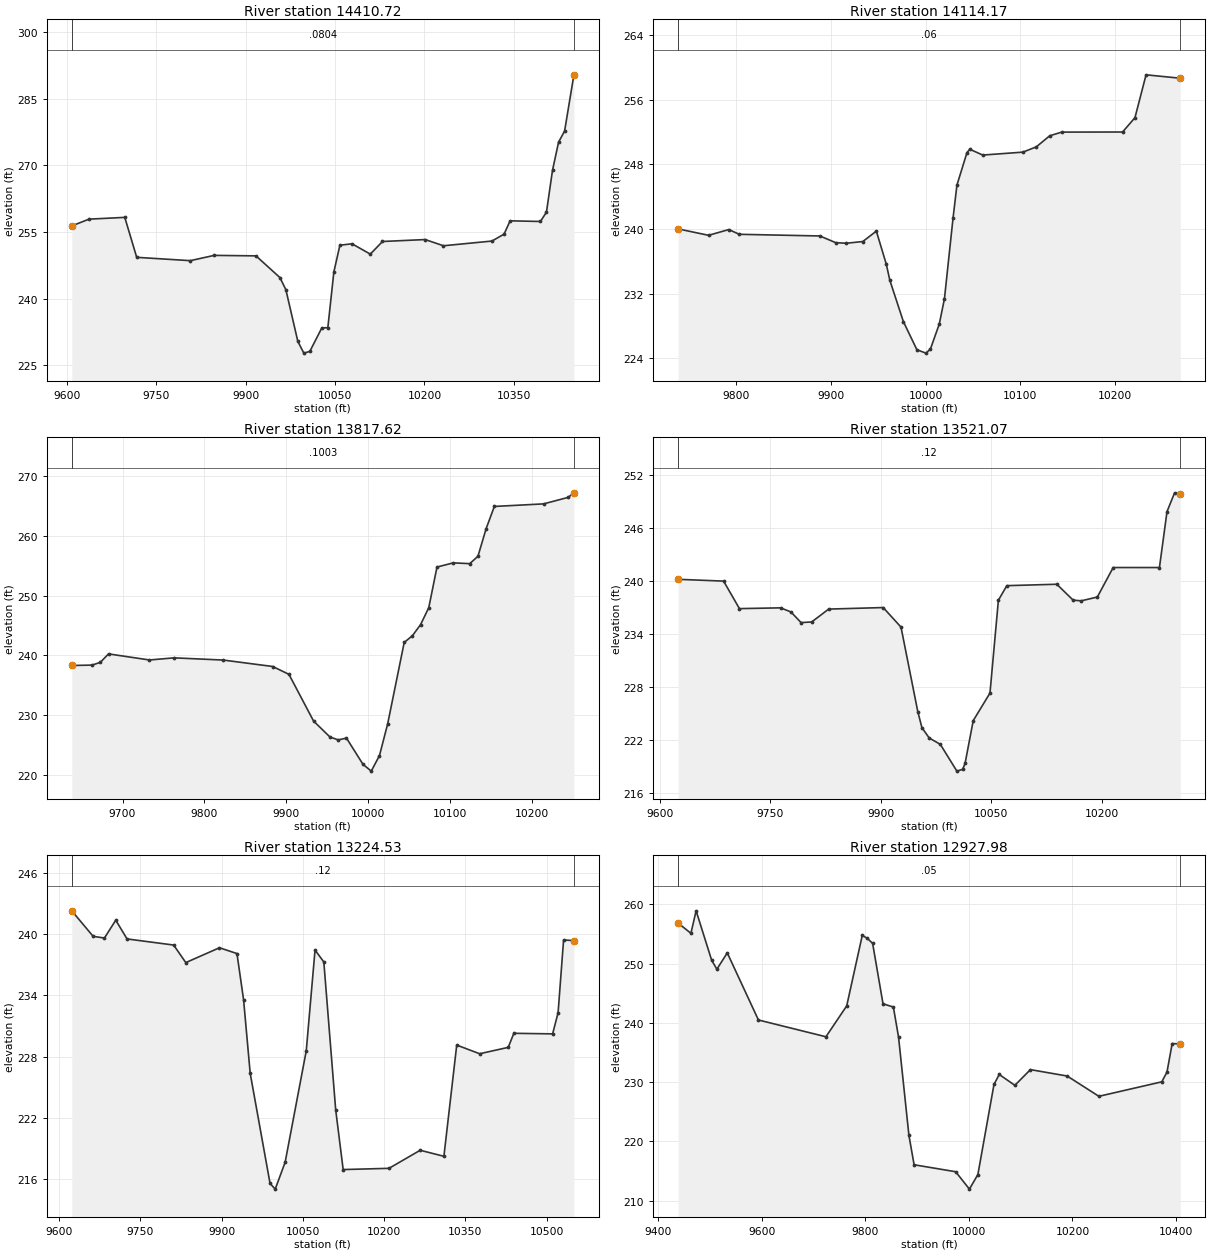
Type RM Length L Ch R = 1 ,14410.72,296.547500,296.547500,296.547500
XS GIS Cut Line= 6
809516.140609675805326.787375871809631.522345222805332.532348653
809747.315118366805331.373382365809906.473236287805319.086805905
809973.122805081805310.092230523810350.349625501805235.549821464
#Sta/Elev= 30
9608.033256.35079636.928257.87599697.002258.27639717.027 249.2769807.039248.5268
9847.059 249.7179917.223249.60569957.338244.72669967.383241.98899987.474230.3388
 9997.52227.697910007.59228.087810027.72233.374410037.83233.431310047.94245.9753
10058.05251.999310078.41252.329610109.11249.998210129.57 252.845 10201.2253.2813
10231.89251.8818 10313.3252.944110333.63254.503810343.79 257.502 10394.6257.3514
10404.76259.448110414.92268.866910425.08  275.2110435.24277.730710450.84290.3876
#Mann= 3 , 0 , 0
9608.033  0.0804       09608.033  0.0804       010450.84  0.0804       0
#XS Ineff= 2 , 0
       0                               0
Bank Sta=9608.033,10450.84
Exp/Cntr=0.3,0.1

Type RM Length L Ch R = 1 ,14114.17,296.547500,296.547500,296.547500
XS GIS Cut Line= 6
809884.614898209805676.929227147809953.488988533805650.354074186
810011.410918893805610.245444854810191.381503241805427.421739844
810226.026612171805397.873691248810296.317849327805353.355503124
#Sta/Elev= 30
9738.868240.00169770.931239.20989792.298239.92189803.371239.33439888.432239.1281
9905.174238.29829916.449 238.2299933.734238.44039948.013239.72859958.475 235.661
9962.293233.63319976.572  228.539990.852225.045310000.48224.632710005.16225.1583
10014.48228.241210019.91231.370110028.93 241.29210033.08245.420810043.68249.4475
10046.69249.8578 10060.3249.138910102.65249.499910116.89250.154410131.01251.5254
10143.75251.980110207.91251.991810220.99253.768510232.69259.066610268.84258.6459
#Mann= 3 , 0 , 0
9738.868    0.06       09738.868    0.06       010268.84    0.06       0
#XS Ineff= 2 , 0
       0                               0
Bank Sta=9738.868,10268.84
Exp/Cntr=0.3,0.1

Type RM Length L Ch R = 1 ,13817.62,296.547500,296.547500,296.547500
XS GIS Cut Line= 6
809890.180043584805744.505992344810025.789639474805747.387226017
810171.844433456805739.201184489 810295.04382737805752.176653716
 810364.51434944805754.383816222810501.971887651805747.510392109
#Sta/Elev= 30
9638.006238.29619662.854238.36299672.862238.8255 9682.87240.23659732.907 239.219
9762.911239.57549823.037239.20589883.393238.1271 9903.19236.81169933.224229.0029
9953.274226.32599963.352225.84649973.437226.14339993.607221.752510003.68 220.617
10013.73  223.2310023.79228.570710043.91242.156710053.91243.277810063.92245.1455
10073.92247.978810083.93254.775610103.94255.474410123.95255.340610133.95256.5805
10143.96261.205210153.97264.915310214.05265.343910244.12266.434610251.11267.1951
#Mann= 3 , 0 , 0
9638.006  0.1003       09638.006  0.1003       010251.11  0.1003       0
#XS Ineff= 2 , 0
       0                               0
Bank Sta=9638.006,10251.11
Exp/Cntr=0.3,0.1

Type RM Length L Ch R = 1 ,13521.07,296.547500,296.547500,296.547500
XS GIS Cut Line= 6
809894.017213564805791.100199194810010.516450294805853.696732559
 810130.84684145806002.752618303810158.502786752806023.688258635
 810333.73801894806113.242724157810452.556026874806150.567176778
#Sta/Elev= 30
9624.702240.16479686.375239.96279707.879236.84939763.775236.93669777.812236.4712
9791.558 235.2669806.006235.34149829.052236.79599903.041236.96979927.223234.7586
9950.002225.1986 9955.61223.37679965.534222.20389980.622221.483410003.09 218.454
10010.94218.6594 10014.2219.324910025.31 224.17510048.02227.289410059.45237.8003
10070.88239.447210138.76239.608910160.92237.8076   10172237.732310193.78238.1629
10215.28241.5001 10278.1241.499110288.38247.831310298.66249.956510306.43249.8784
#Mann= 3 , 0 , 0
9624.702    0.12       09624.702    0.12       010306.43    0.12       0
#XS Ineff= 2 , 0
       0                               0
Bank Sta=9624.702,10306.43
Exp/Cntr=0.3,0.1

Type RM Length L Ch R = 1 ,13224.53,296.547500,296.547500,296.547500
XS GIS Cut Line= 6
809586.352182007805916.148079014809829.934139482806008.941111886
809935.959475026806083.551634288810019.602431375806176.873220103
810149.001972984806257.981065655810393.847392719806330.047459744
#Sta/Elev= 30
9623.378242.3145 9662.84239.80889683.703239.6409 9704.58 241.3969725.456239.5529
9811.469238.95179833.908237.22829896.108238.68629928.384238.11559940.598233.5751
9952.812226.34529989.454215.5318    9999214.968710017.35217.612710056.31228.5561
10072.53238.459110088.74237.290810110.67222.756910124.46216.890910209.09217.0124
10266.73218.788510310.46218.193510334.15229.122310376.49228.271710429.22228.8977
10439.61230.2803 10511.2230.224110521.31232.309310531.43239.451610550.49239.3898
#Mann= 3 , 0 , 0
9623.378    0.12       09623.378    0.12       010550.49    0.12       0
#XS Ineff= 2 , 0
       0                10083.51       0
Bank Sta=9623.378,10550.49
Exp/Cntr=0.3,0.1

Type RM Length L Ch R = 1 ,12927.98,148.273800,148.273800,148.273800
XS GIS Cut Line= 6
809420.463273068806377.394955107809942.994941646 806343.06470053
810016.725244566806319.461370864810069.290701233806313.080663912
  810263.1913348806345.816355991 810380.63313917806359.184874115
#Sta/Elev= 30
9438.503256.84329463.113255.11989473.143 258.9139503.232250.55499513.262249.0601
9533.322251.81549593.501240.4906 9723.89237.65999764.009242.87219794.068254.7741
9804.078254.25139814.088253.41249834.107243.22579854.126242.67419864.136237.5994
9884.156221.02019894.165216.0595 9974.43 214.884   10001211.947510017.35214.4078
10048.45229.613410058.62231.297310088.77229.4641 10118.8232.114710189.84 231.034
10251.07227.611910372.56230.056610382.59231.705310392.62236.522910408.31236.4188
#Mann= 3 , 0 , 0
9438.503    0.05       09438.503    0.05       010408.31    0.05       0
#XS Ineff= 2 , 0
       0                               0
Bank Sta=9438.503,10408.31
Exp/Cntr=0.3,0.1

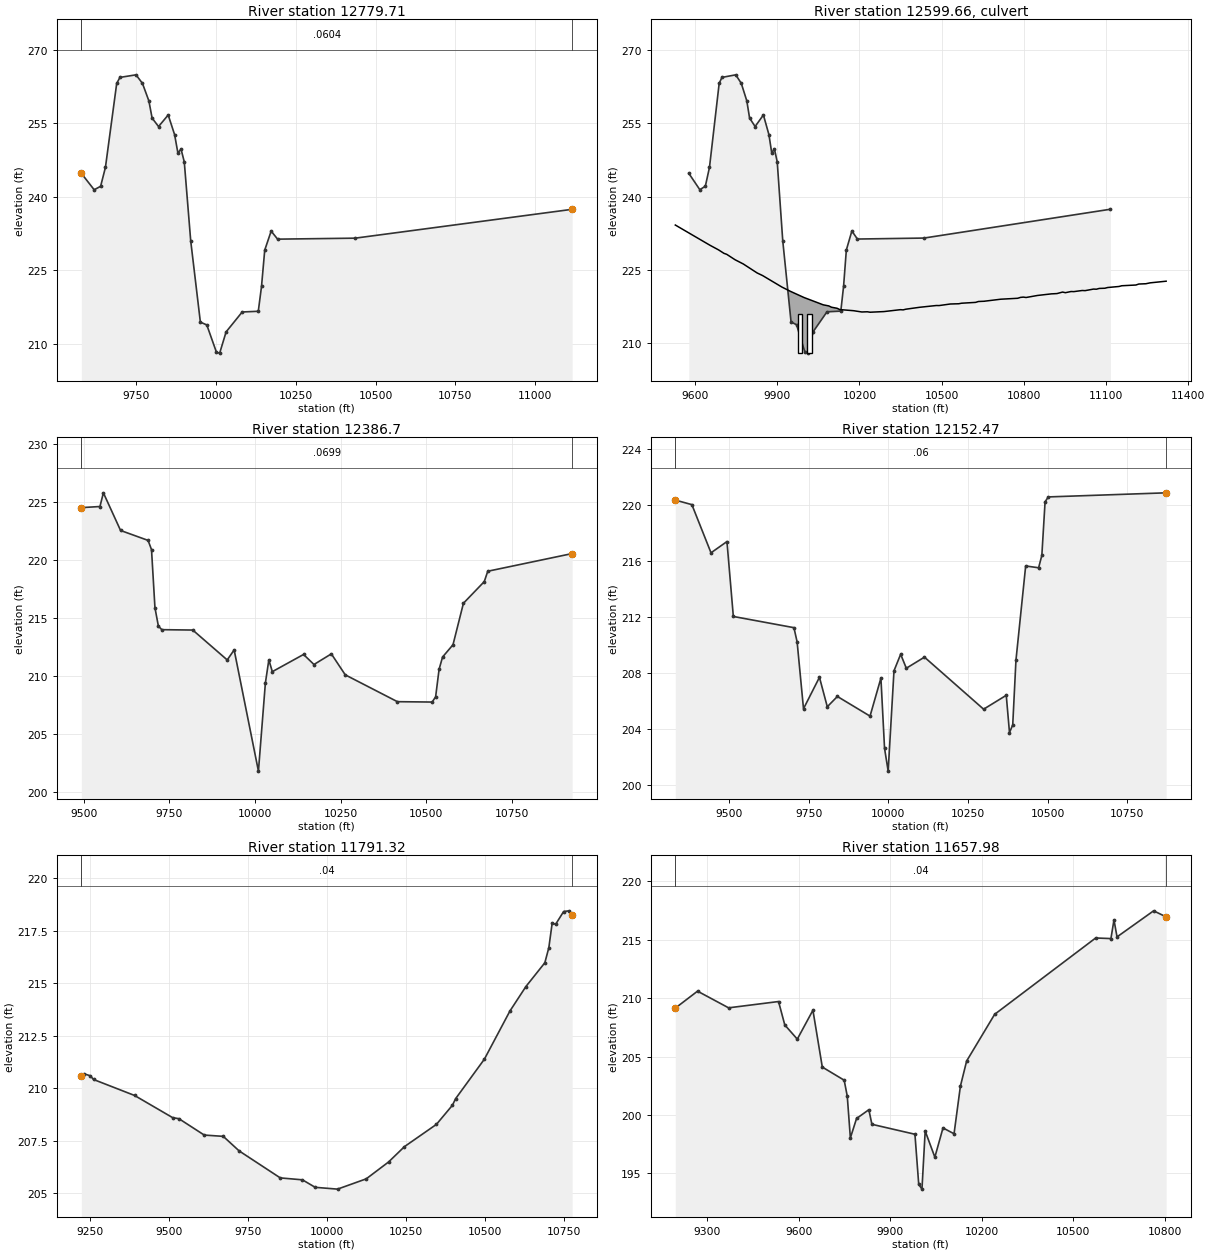
Type RM Length L Ch R = 1 ,12779.71,393.004500,393.004500,393.004500
XS GIS Cut Line= 3
809485.076979518806394.978364632810186.171605289806488.786800459
811005.761097282806629.499454215
#Sta/Elev= 30
9577.351244.75459617.629241.40029637.808242.10729652.917245.97279688.253263.1191
9698.342 264.3499748.788264.87549768.966263.13479789.144259.54559799.233 256.046
9819.412254.30979849.679256.67549869.857252.64329879.946248.95799890.036249.6825
9900.125247.09699920.303230.9545 9950.57214.36839970.748213.793510001.02208.2067
 10011.1208.036110031.28212.377910081.73216.440410132.17216.584310142.26221.6445
10152.35229.075910172.53232.960110192.71231.3157 10435.7231.515311116.27237.4082
#Mann= 3 , 0 , 0
9577.351  0.0604       09577.351  0.0604       011116.27  0.0604       0
#XS Ineff= 2 , 0
       0                10100.28       0
Bank Sta=9577.351,11116.27
Exp/Cntr=0.3,0.1

Type RM Length L Ch R = 2 ,12599.66,,,
Bridge Culvert--1,0,-1,-1, 0
Deck Dist Width WeirC Skew NumUp NumDn MinLoCord MaxHiCord MaxSubmerge Is_Ogee
96.502,200,2.6,0, 60, 60, , , 0.95, 0, 0,0,,
 9528.20 9655.45 9685.66 9705.79 9715.86 9746.07 9776.28 9826.63 9846.77 9917.25
 9947.41 9997.6910068.0810088.1910098.2510118.3610128.4110178.6910208.8610228.97
10239.0210289.3010349.6310359.6910369.7410420.0210480.6310490.8810531.8410562.57
10572.8110624.0210634.2710654.7510716.2010777.6610787.9010798.1410808.3810849.35
10900.5610921.0510941.5310951.7810972.2610982.5011013.3011023.6011054.5311064.84
11075.1411095.7611106.0711147.3011157.6111209.1411219.4511245.4311260.6811319.42
  234.18  230.02  229.11  228.39  228.19  227.09  226.22  224.39  223.85  221.50
  220.65  219.37  217.87  217.65  217.38  217.17  216.90  216.67  216.41  216.45
  216.36  216.49  216.88  216.84  216.98  217.37  217.73  217.72  218.04  218.09
  218.20  218.37  218.55  218.60  219.02  219.21  219.39  219.45  219.37  219.78
  220.11  220.17  220.48  220.35  220.59  220.57  220.80  220.77  221.09  221.06
  221.22  221.26  221.41  221.62  221.77  221.92  222.12  222.18  222.36  222.70
                                                                                
                                                                                
                                                                                
                                                                                
                                                                                
                                                                                
 9528.20 9655.45 9685.66 9705.79 9715.86 9746.07 9776.28 9826.63 9846.77 9917.25
 9947.41 9997.6910068.0810088.1910098.2510118.3610128.4110178.6910208.8610228.97
10239.0210289.3010349.6310359.6910369.7410420.0210480.6310490.8810531.8410562.57
10572.8110624.0210634.2710654.7510716.2010777.6610787.9010798.1410808.3810849.35
10900.5610921.0510941.5310951.7810972.2610982.5011013.3011023.6011054.5311064.84
11075.1411095.7611106.0711147.3011157.6111209.1411219.4511245.4311260.6811319.42
  234.18  230.02  229.11  228.39  228.19  227.09  226.22  224.39  223.85  221.50
  220.65  219.37  217.87  217.65  217.38  217.17  216.90  216.67  216.41  216.45
  216.36  216.49  216.88  216.84  216.98  217.37  217.73  217.72  218.04  218.09
  218.20  218.37  218.55  218.60  219.02  219.21  219.39  219.45  219.37  219.78
  220.11  220.17  220.48  220.35  220.59  220.57  220.80  220.77  221.09  221.06
  221.22  221.26  221.41  221.62  221.77  221.92  222.12  222.18  222.36  222.70
                                                                                
                                                                                
                                                                                
                                                                                
                                                                                
                                                                                
BR Coef=-1 , 0 , 0 ,, 0 ,,,0.8,-1,,0,
WSPro=,,,, 1 ,,,, 0 ,,,, 0 ,,,,-1 ,-1 ,-1 , 0 , 0 , 0 , 0 , 0
Multiple Barrel Culv=2,8,17,200,0.013,0.7,1,8,3,208,203,2,Culvert #1, 0, 96.502
 9983.00 9983.0010017.0010017.00
Culvert Bottom n=0.013
BC Design=,, 0 ,, 0 ,,,,,,

Type RM Length L Ch R = 1 , 12386.7,234.235000,234.235000,234.235000
XS GIS Cut Line= 4
809620.852347195806701.090102628 810025.00000003806737.295024112
810257.762253642806775.149394065811037.853456944806910.924761727
#Sta/Elev= 30
9493.011224.47959547.375224.57559557.415 225.7549607.615222.51369687.936221.6582
9697.976220.86179708.016215.85679718.056 214.2769728.096213.97269818.456213.9401
9919.039 211.3679939.302212.227610010.22201.794210030.48209.375110040.62211.3757
10050.75210.357210141.94211.838110172.39210.973710223.15211.889210263.75210.0836
   10416207.773410517.51207.741510527.66 208.19110537.81210.567210547.96211.6177
10578.41212.675210608.86216.246810669.76218.111610679.91219.002610926.42220.5253
#Mann= 3 , 0 , 0
9493.011  0.0699       09493.011  0.0699       010926.42  0.0699       0
#XS Ineff= 2 , 0
       09898.229        10076.69       0
Bank Sta=9493.011,10926.42
Exp/Cntr=0.3,0.1

Type RM Length L Ch R = 1 ,12152.47,361.142000,361.142000,361.142000
XS GIS Cut Line= 4
 809643.07013464807007.201840624 810099.76909858807024.482341945
810408.349479586806856.614614666811129.193249732 806982.51541014
#Sta/Elev= 30
9331.794 220.3799383.761220.05289443.804216.6083 9493.84217.41289513.854212.0561
 9703.99211.25559713.997210.23769734.012205.45829784.047207.70679808.663205.5995
 9840.31206.33689942.766204.93059976.917207.64849988.301202.62449999.685 200.997
10017.93 208.17110038.85209.3546 10056.6208.354510113.52209.147910299.13205.4252
10370.19206.418610380.34203.754210390.49204.300410400.64 208.931 10431.1215.6675
 10471.7215.539410481.85216.4221   10492220.257510502.15220.604910871.86220.8977
#Mann= 3 , 0 , 0
9331.794    0.06       09331.794    0.06       010871.86    0.06       0
#XS Ineff= 2 , 0
       09985.379        10076.01       0
Bank Sta=9331.794,10871.86
Exp/Cntr=0.3,0.1

Type RM Length L Ch R = 1 ,11791.32,133.341100,133.341100,133.341100
XS GIS Cut Line= 6
 809766.50228703807083.729775101809924.495442152807083.729775101
810457.722340554807113.353491709810800.863724291807157.789066568
811200.783898145807217.036499709 811304.46690616807254.066145435
#Sta/Elev= 30
9223.493210.57879231.991210.68579251.991 210.5899261.991210.41469392.005209.6515
9512.161208.59659532.187208.54539612.292207.76549672.377207.70449722.468207.0124
9852.705205.7246 9922.88205.63249963.213205.2754 10033.8205.189710124.55205.6793
10195.13206.481910245.55207.2153 10346.6208.274910397.15209.185410407.26209.4993
10498.24211.381610579.11 213.67710629.66214.843610689.51215.975610702.17216.6981
10712.78 217.875 10723.4217.804410748.97218.417110765.88218.450210775.93218.2493
#Mann= 3 , 0 , 0
9223.493    0.04       09223.493    0.04       010775.93    0.04       0
#XS Ineff= 2 , 0
       09873.981        10085.48       0
Bank Sta=9223.493,10775.93
Exp/Cntr=0.3,0.1

Type RM Length L Ch R = 1 ,11657.98,173.509000,173.509000,173.509000
XS GIS Cut Line= 6
809713.428387669807351.536416554810364.229413553 807221.62043364
810431.729099073807229.456460322  810786.0103649807321.906246306
811027.538258302807340.535761679  811296.1083669807340.842287178
#Sta/Elev= 30
9194.968209.14549267.879210.59779369.749209.17059533.614209.71049554.118207.7035
9595.126206.49069646.385208.9646 9677.14204.09889748.903202.97489759.068201.6049
9769.207198.03029789.485199.69589829.845200.44759839.868199.19869981.024198.3462
9993.471194.053910004.05193.648510014.63198.621110046.36196.382710073.08198.8887
10109.33198.387610130.12202.458210150.62204.6182 10242.5208.614410573.94215.1513
10623.95215.099910633.95216.695610643.95215.243110763.96 217.47610805.07216.9571
#Mann= 3 , 0 , 0
9194.968    0.04       09194.968    0.04       010805.07    0.04       0
#XS Ineff= 2 , 0
       09937.132                       0
Bank Sta=9194.968,10805.07
Exp/Cntr=0.3,0.1

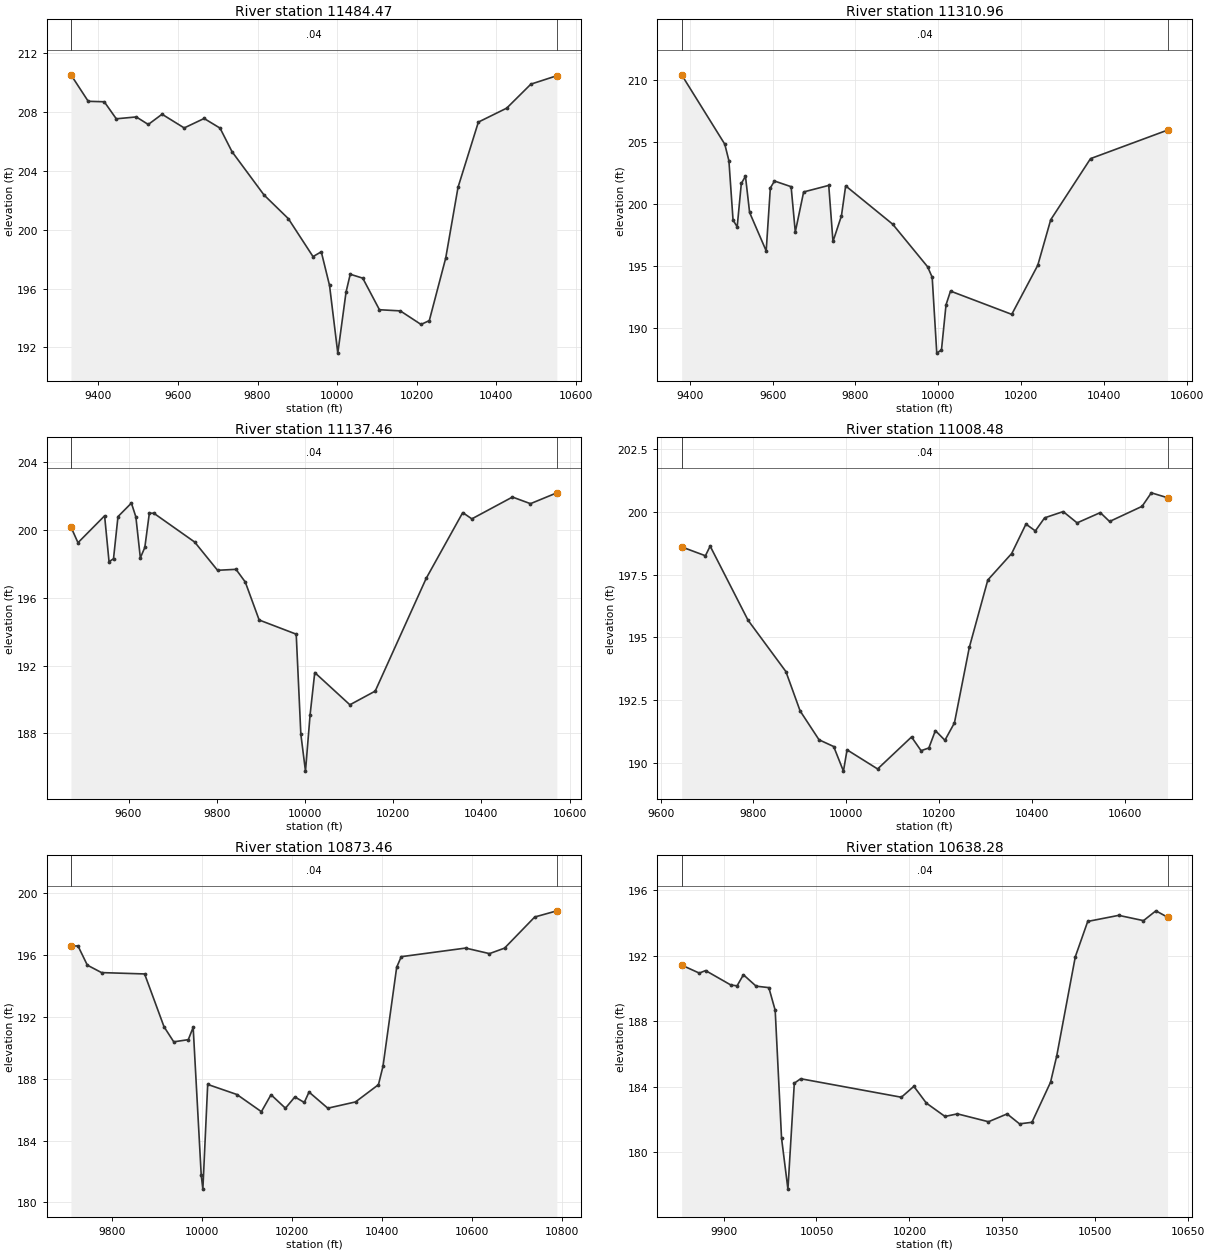
Type RM Length L Ch R = 1 ,11484.47,173.508900,173.508900,173.508900
XS GIS Cut Line= 6
 809781.95932911 807393.55297995810009.421965889807367.518771843
810222.882415258807365.168678868810341.108839498807386.268051794
810728.966600119807498.232080878810979.695296349807541.429066561
#Sta/Elev= 30
9331.007210.52719374.394208.72729414.717208.69569444.899207.53819495.181207.6643
 9525.35207.15249559.966207.8483 9615.63206.91719665.707207.55939705.714206.9047
9735.737205.30589816.213  202.369877.409200.74899939.424  198.179960.174198.4973
9980.923196.209110001.67191.608710022.46195.767310032.95196.9711 10064.4 196.705
10106.34194.558710158.77194.480710210.84193.558910231.65193.818210272.93198.0728
10303.84202.878510354.98207.3138 10426.2208.262210487.01209.893610552.24 210.466
#Mann= 3 , 0 , 0
9331.007    0.04       09331.007    0.04       010552.24    0.04       0
#XS Ineff= 2 , 0
       0                               0
Bank Sta=9331.007,10552.24
Exp/Cntr=0.3,0.1

Type RM Length L Ch R = 1 ,11310.96,173.509000,173.509000,173.509000
XS GIS Cut Line= 6
809780.854742053807485.233707157810036.578399357807490.469850898
810210.583569236807520.153560123810297.900306033807544.491132048
810631.540802483807663.021997249810920.316845298807727.661481134
#Sta/Elev= 30
9380.241210.39219484.411204.81789494.411203.48739504.411198.71979514.412 198.166
9524.416201.65889534.422202.23739544.427199.32379584.497196.23579594.522 201.298
9604.547201.85249644.703201.39819654.793197.75419674.972200.97439735.625201.5004
9745.841 196.9919766.272199.04879776.488201.46429890.093198.38279974.427194.9594
9985.521194.11749996.615188.015110007.95188.271610018.98191.901510029.79193.0029
10177.74191.132710240.64195.081110271.91198.739710368.09203.654410554.11205.9468
#Mann= 3 , 0 , 0
9380.241    0.04       09380.241    0.04       010554.11    0.04       0
#XS Ineff= 2 , 0
       0                               0
Bank Sta=9380.241,10554.11
Exp/Cntr=0.3,0.1

Type RM Length L Ch R = 1 ,11137.46,128.974200,128.974200,128.974200
XS GIS Cut Line= 6
809819.151433863807621.209589138809909.050831095807630.817943151
810072.294904797807662.942374112810616.617063439807834.813480667
810709.175198572807859.076629626810884.116427994807891.763842156
#Sta/Elev= 30
9469.504200.16999485.412199.24229545.769 200.829 9555.85198.11759565.966198.2989
9576.104200.78189606.518201.58159616.656200.76419626.795198.34979636.941198.9628
9647.185200.9829 9657.43200.98049749.927199.28229801.807197.6158 9843.67 197.672
9864.667196.92289896.161194.68349980.147193.84789990.645187.946510001.15185.7702
10011.66189.107810022.17191.583810101.81189.6827 10159.2190.489710274.69197.1346
10357.62201.0177 10378.3200.649210470.35201.935410511.17201.544810570.98202.1846
#Mann= 3 , 0 , 0
9469.504    0.04       09469.504    0.04       010570.98    0.04       0
#XS Ineff= 2 , 0
       0                               0
Bank Sta=9469.504,10570.98
Exp/Cntr=0.3,0.1

Type RM Length L Ch R = 1 ,11008.48,135.025800,135.025800,135.025800
XS GIS Cut Line= 5
 809944.78726235807787.420732319810235.331652194807846.301821277
810403.287545294807901.321855232810673.561396271 807965.02926296
 810969.89736858807962.133471698
#Sta/Elev= 30
9645.397 198.598 9696.63 198.2479706.833198.6297 9788.46195.68729870.086193.6466
9900.696192.08499941.509190.93659973.067190.66869994.113189.691610001.91190.5371
10067.77189.777710140.89191.048710161.44190.5027 10178.2190.611910192.26191.3006
10212.81190.917710233.36191.608510265.38194.604910305.28197.284410356.65198.3353
10387.47199.504510407.71199.233710427.71199.753410467.71200.001510497.71199.5529
10547.71199.960810567.71199.608110637.72200.209710657.72200.746610692.62200.5522
#Mann= 3 , 0 , 0
9645.397    0.04       09645.397    0.04       010692.62    0.04       0
#XS Ineff= 2 , 0
       0                               0
Bank Sta=9645.397,10692.62
Exp/Cntr=0.3,0.1

Type RM Length L Ch R = 1 ,10873.46,235.172600,235.172600,235.172600
XS GIS Cut Line= 6
809959.938084825 807886.32734159 810089.60887481807927.674509688
810406.510512765 808055.52657595810577.025129338808101.188754233
 810695.40029803808119.799334041810989.202643663808040.319835737
#Sta/Elev= 30
9709.296196.57789724.916196.58769745.656195.3445 9777.21194.86299872.834194.7752
 9915.97191.35889937.538 190.383 9969.89190.52419980.674191.32159998.596181.7479
10002.22180.854610012.95187.628110077.93 186.97510132.18185.864610153.55186.9617
10185.59186.089410206.55186.819510227.47186.459710237.93 187.13510279.66186.0906
10341.24186.496410392.16187.612110402.28188.811510432.65  195.2110442.78 195.892
10585.69 196.44910638.68  196.0910672.17196.445310739.15198.458110788.31198.8585
#Mann= 3 , 0 , 0
9709.296    0.04       09709.296    0.04       010788.31    0.04       0
#XS Ineff= 2 , 0
       0                10276.46       0
Bank Sta=9709.296,10788.31
Exp/Cntr=0.3,0.1

Type RM Length L Ch R = 1 ,10638.28,235.172500,235.172500,235.172500
XS GIS Cut Line= 6
809976.848068179808169.196418626810065.418533516808184.272361257
810235.427946583808222.509985105 810363.98749185808239.933339954
810535.920009561808252.077215447810753.805830169808255.248690422
#Sta/Elev= 30
9832.413191.41639860.902190.92889871.058191.08289911.684190.2057 9921.84190.1514
9932.093190.82799952.608190.13149973.123190.04299983.381188.66189993.638 180.864
10003.94177.750510014.24 184.21210024.54184.484410187.05183.355810207.19184.0211
10227.32182.999210257.44182.184410277.51182.341710327.65181.8614 10357.7 182.339
10377.73181.732510397.76 181.82710427.78184.269110437.78185.875210467.79191.9301
 10487.8194.080910537.81194.451310577.81194.129110597.81194.727510616.61194.3395
#Mann= 3 , 0 , 0
9832.413    0.04       09832.413    0.04       010616.61    0.04       0
#XS Ineff= 2 , 0
       0                 10309.3       0
Bank Sta=9832.413,10616.61
Exp/Cntr=0.3,0.1

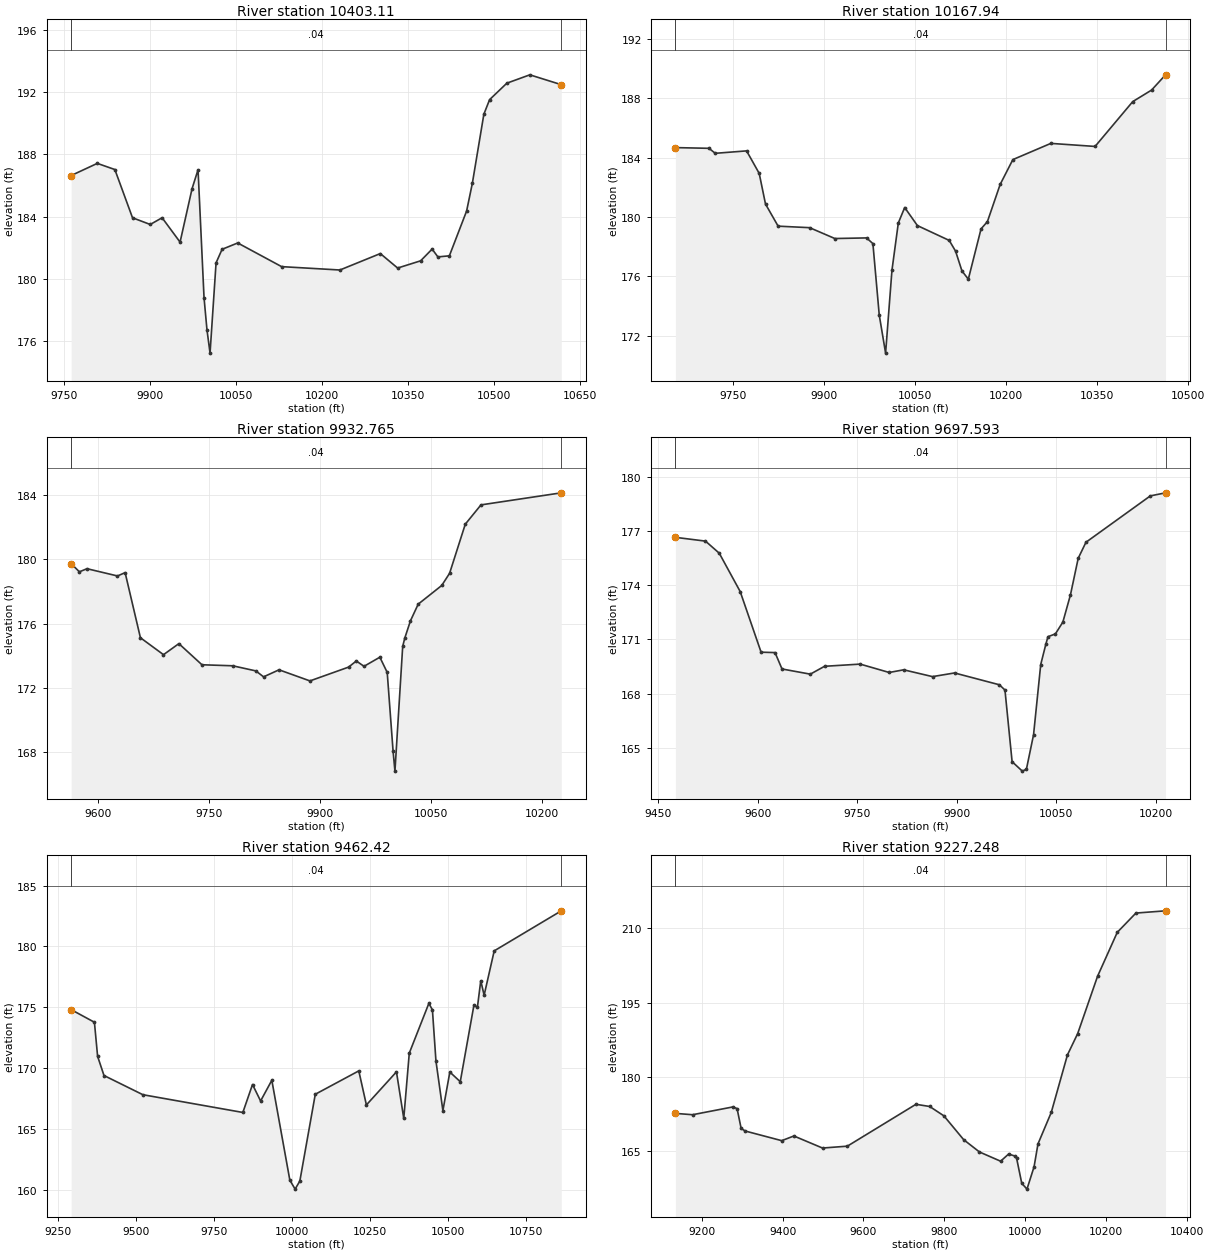
Type RM Length L Ch R = 1 ,10403.11,235.172600,235.172600,235.172600
XS GIS Cut Line= 6
 809940.18903767808490.210631506810088.175777415808456.920649541
 810272.27831622808400.285253174810369.770335844808379.443821764
810493.667274478808362.588060045810779.752252229808336.294098256
#Sta/Elev= 30
9761.735186.6392 9807.39187.41879838.073187.02349868.917183.92829899.877183.4993
9920.618  183.939952.021182.36599972.956185.79379983.424187.01049993.892 178.799
    9999176.749510004.39175.244310014.91181.036910025.42181.905710052.75182.3125
10129.46 180.79410231.29180.577610301.93181.6318 10332.2180.703610372.37181.1674
10392.46  181.92 10402.5181.418710422.58181.487410452.71184.362210462.75186.1427
10482.84190.571610492.88191.508610523.01192.563910563.17193.100310618.16192.4684
#Mann= 3 , 0 , 0
9761.735    0.04       09761.735    0.04       010618.16    0.04       0
#XS Ineff= 2 , 0
       09968.664        10288.58       0
Bank Sta=9761.735,10618.16
Exp/Cntr=0.3,0.1

Type RM Length L Ch R = 1 ,10167.94,235.172500,235.172500,235.172500
XS GIS Cut Line= 6
809911.164225272808746.630787163810011.060262646808722.309150371
810174.197339087808676.181614854 810440.07436903808592.843298901
810559.931536884808557.168086193810687.249993829808523.414919124
#Sta/Elev= 30
9654.852184.67689710.193184.62939720.501184.29219772.158184.45619792.942182.9389
9803.334180.87229824.119179.38049876.079179.27849917.647178.54639969.876178.5883
9980.333178.20339990.791173.385410001.25  170.8210011.74176.408910022.23179.5982
10032.72180.636210053.69179.418710106.13178.418810116.62177.6906 10127.1176.3607
10137.59175.805610158.57179.197410169.05179.687310190.03182.191610210.98183.8681
10273.58184.961210346.48184.755510408.55187.778210439.59188.555710462.61189.5839
#Mann= 3 , 0 , 0
9654.852    0.04       09654.852    0.04       010462.61    0.04       0
#XS Ineff= 2 , 0
       09916.263                       0
Bank Sta=9654.852,10462.61
Exp/Cntr=0.3,0.1

Type RM Length L Ch R = 1 ,9932.765,235.172600,235.172600,235.172600
XS GIS Cut Line= 6
809894.214763813809000.872709067809976.526116071808980.106316057
 810120.10312167808938.620300504810314.486336311808879.177381188
810459.756934631808828.464313171810526.058764966808800.956298823
#Sta/Elev= 30
 9563.39179.73839574.513179.23099584.826179.4246 9626.08178.97249636.393179.1798
9657.101175.12519688.328174.06959709.146174.75729740.374173.4414 9782.01173.3776
9813.309173.05899823.766172.6887 9844.68173.12719886.508172.43589938.793173.2949
 9949.25173.67619959.707173.34529981.114173.91199991.078172.9652    9999168.0711
10001.54166.816610012.03174.581610014.77 175.08910022.53176.179210033.02177.2169
10064.87  178.3810075.49179.137610096.73182.196710117.97183.399410226.67184.1505
#Mann= 3 , 0 , 0
 9563.39    0.04       0 9563.39    0.04       010226.67    0.04       0
#XS Ineff= 2 , 0
       09858.741                       0
Bank Sta=9563.39,10226.67
Exp/Cntr=0.3,0.1

Type RM Length L Ch R = 1 ,9697.593,235.172600,235.172600,235.172600
XS GIS Cut Line= 6
 809901.10414229809287.445301408810069.116633807809236.821309584
810171.584156301809196.469410872810422.150330423809088.722010254
  810476.3662405809058.621532827810573.898592958808991.545703877
#Sta/Elev= 30
9476.021176.64319521.362 176.4349542.116175.76699573.653173.6492 9605.19170.2967
9626.215170.27479636.727169.36889679.385 169.083 9700.88169.51739754.617169.6379
9798.274169.17549820.168169.3224 9863.62168.94679896.797169.14899964.409168.4961
9972.826168.20559983.602164.2463    9999163.724310005.15 163.82610015.95165.7368
10026.76169.615510034.48170.738910037.68171.1522 10048.9171.308610060.13171.9613
10071.56173.462610083.25175.485610094.94176.371110191.97178.933110214.91179.1026
#Mann= 3 , 0 , 0
9476.021    0.04       09476.021    0.04       010214.91    0.04       0
#XS Ineff= 2 , 0
       09828.047                       0
Bank Sta=9476.021,10214.91
Exp/Cntr=0.3,0.1

Type RM Length L Ch R = 1 , 9462.42,235.172500,235.172500,235.172500
XS GIS Cut Line= 6
809951.443548064809546.311693319810276.390835689809451.006939193
810446.850874601809338.955102084810808.439414488 809026.46953445
811058.952310746808894.822712359811307.570516841808803.952061551
#Sta/Elev= 30
9291.691174.81469366.261173.77849376.474170.98259396.957169.40699521.666167.8317
9842.338166.37449873.316168.66839899.262167.31719935.272169.01659993.081160.8151
10009.99160.081410025.13160.744810074.68167.868210214.23169.786910238.61166.9909
10335.05169.708510358.47165.886610376.15171.242410438.95 175.32710450.37174.7988
10461.69170.602610483.97166.522510506.26169.691610539.69168.898610583.65175.1992
10594.61174.996610605.45177.187810616.23 175.99610648.56179.638210863.76182.9251
#Mann= 3 , 0 , 0
9291.691    0.04       09291.691    0.04       010863.76    0.04       0
#XS Ineff= 2 , 0
       09738.867        10045.97       0
Bank Sta=9291.691,10863.76
Exp/Cntr=0.3,0.1

Type RM Length L Ch R = 1 ,9227.248,235.172600,235.172600,235.172600
XS GIS Cut Line= 6
809892.603434424809670.432397338810224.504410723 809651.70304406
 810447.39510425809592.037839633810602.652445993809494.196648279
 810772.20750851809321.574985408810958.116380133809203.222875164
#Sta/Elev= 30
9135.086172.55579177.486172.28569277.517173.86979287.524173.52169297.531 169.524
9307.551168.98929397.811 167.0359427.959167.98219498.687165.54219560.049165.9194
9729.598174.39519763.605173.95469798.777172.05459847.533167.2387 9886.63164.7441
9938.921162.87729958.549164.31519974.456163.92149978.288163.54549991.147158.4154
10004.06157.224810021.62161.7489 10031.3166.380810064.12172.755210104.14184.4001
10129.47188.722510178.55200.314410227.27209.206810273.33 213.10710346.57213.5602
#Mann= 3 , 0 , 0
9135.086    0.04       09135.086    0.04       010346.57    0.04       0
#XS Ineff= 2 , 0
       09732.186                       0
Bank Sta=9135.086,10346.57
Exp/Cntr=0.3,0.1