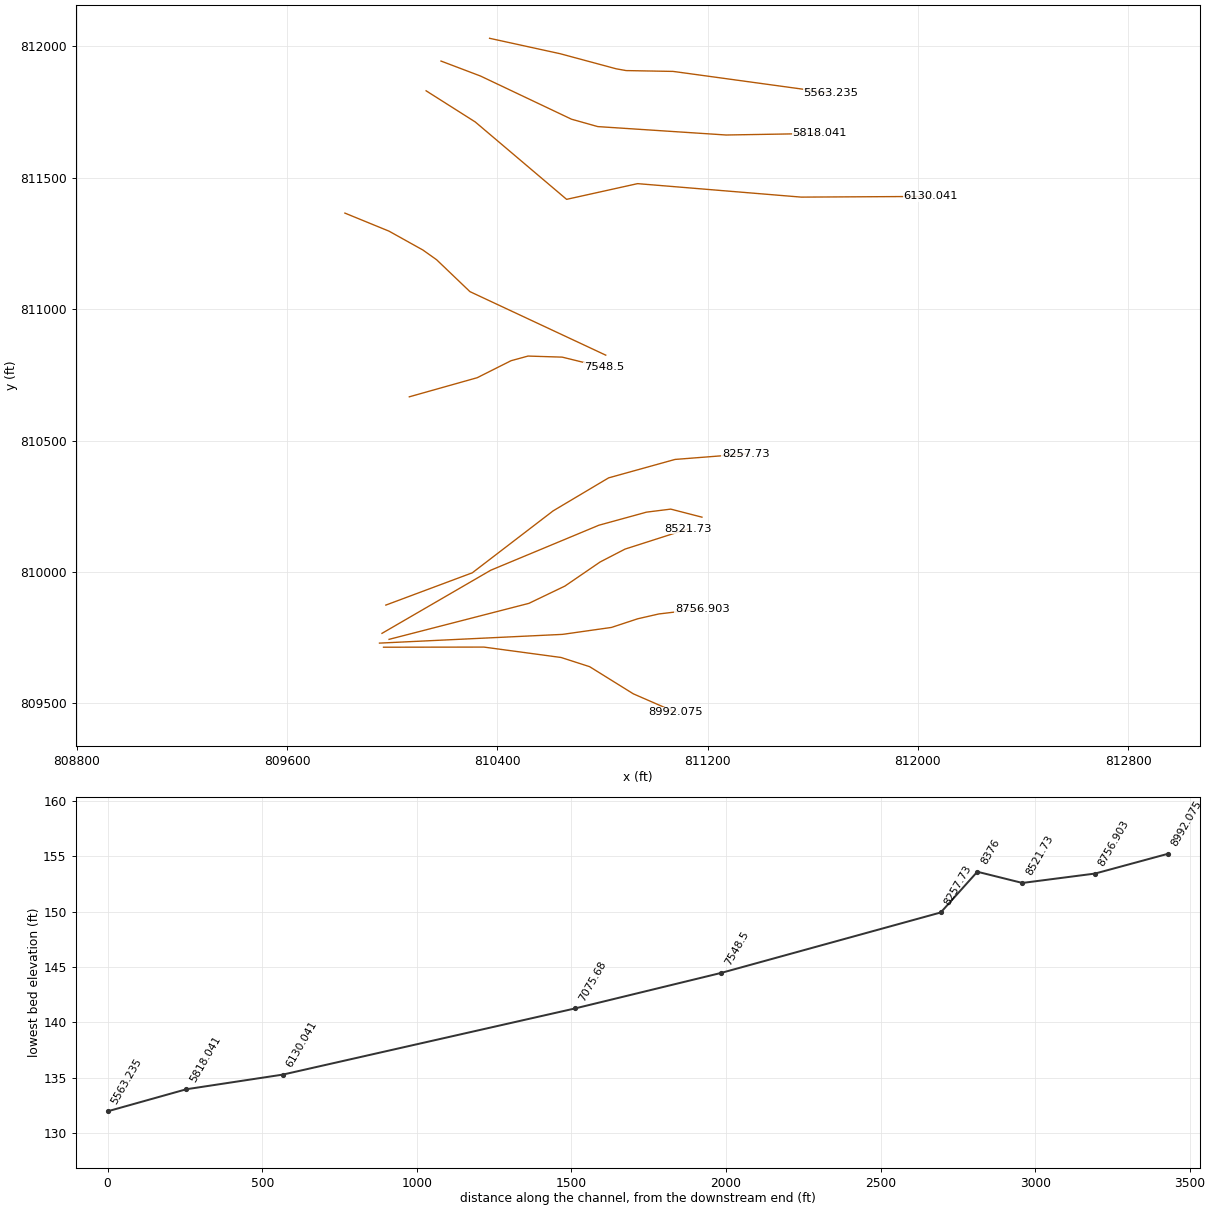
HEC-RAS study 18137_ras.prj: 18137

--- 18137_ras.g01 (geometry) --- (continued)

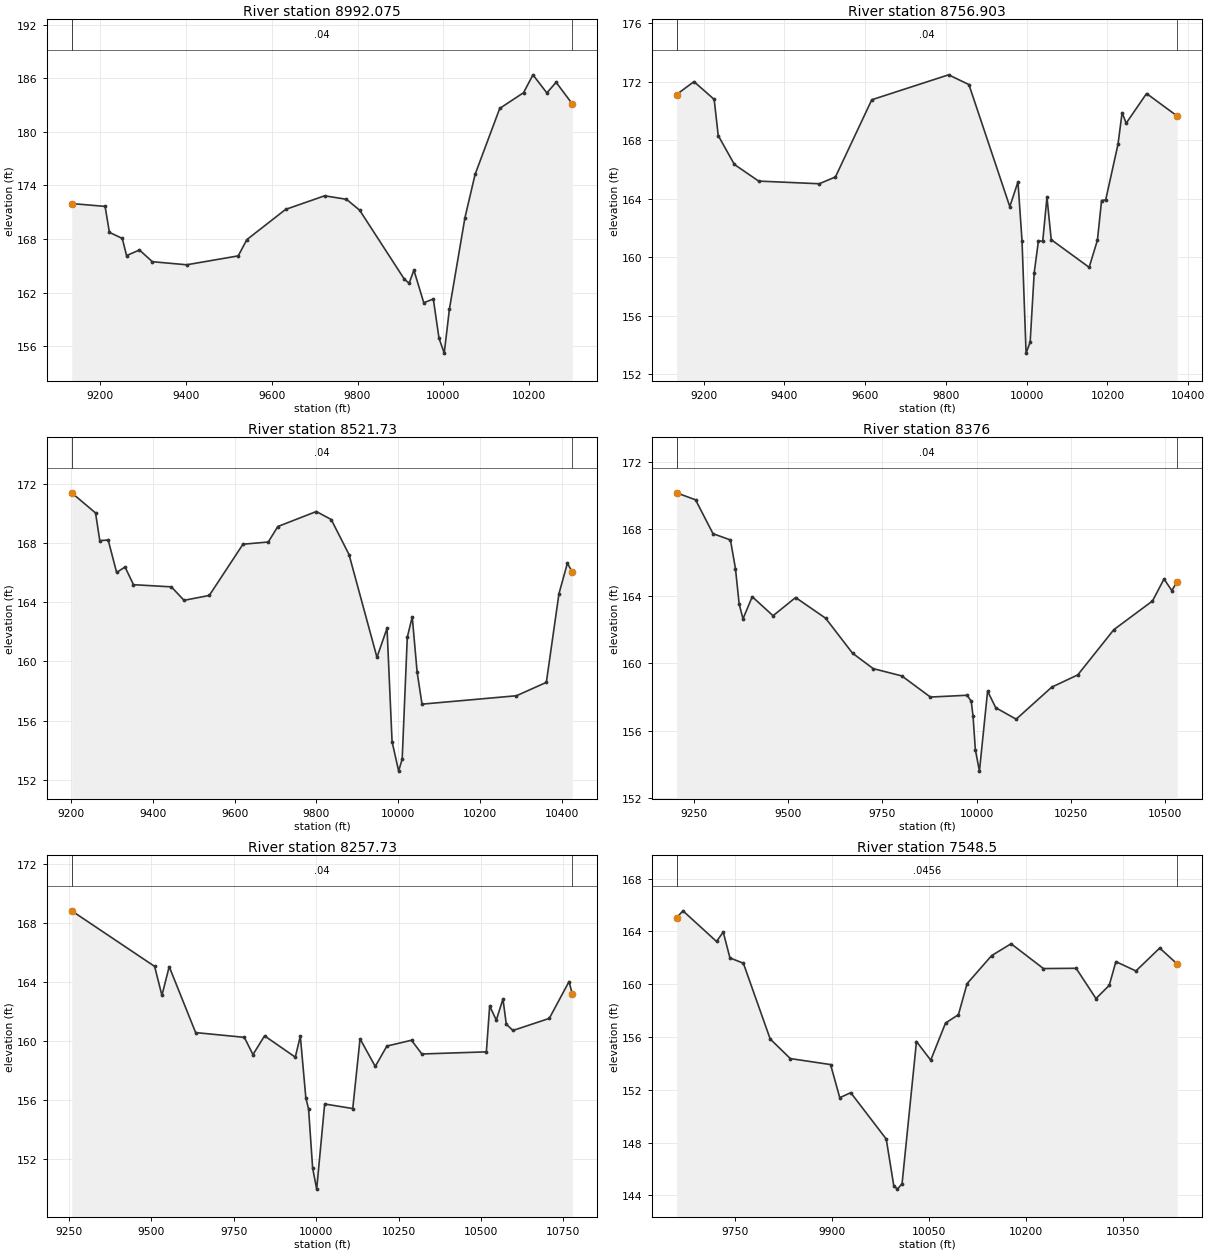
Type RM Length L Ch R = 1 ,8992.075,235.172500,235.172500,235.172500
XS GIS Cut Line= 6
809967.228930517 809713.81869797810349.203826052809714.335143001
810642.803030208809674.775999916810751.508514614809639.773358705
810917.741024752 809536.45785127 811080.07931556809465.753261571
#Sta/Elev= 30
9134.157171.96779211.959171.64699221.963168.74039251.975168.06169261.976166.1358
9291.977166.76519321.979165.45159401.993165.10719522.049166.10399542.104 167.922
9632.473171.31229723.389172.83569774.221172.44149804.864171.22259909.243163.4755
9920.142163.04299931.244164.50529954.206160.85389976.475161.27199989.764 156.871
 10001.9155.209110013.97160.144510050.19170.394510073.82175.240510131.16182.6266
10186.63184.3865 10208.6186.387610240.93  184.3610262.48185.555710300.27183.1218
#Mann= 3 , 0 , 0
9134.157    0.04       09134.157    0.04       010300.27    0.04       0
#XS Ineff= 2 , 0
       09704.663                       0
Bank Sta=9134.157,10300.27
Exp/Cntr=0.3,0.1

Type RM Length L Ch R = 1 ,8756.903,235.172600,235.172600,235.172600
XS GIS Cut Line= 6
809951.972790592 809729.44213621810648.163387913809762.657906629
810834.567411326809789.102866547810934.528937341809822.022343881
811014.582549948809840.333365734811180.626715302809860.165535229
#Sta/Elev= 30
9132.784171.11339175.866171.9936 9225.93170.77899235.942168.30699275.993166.3297
9336.069165.1931 9486.22165.01229526.248165.4763 9616.31170.75449806.592172.4587
9856.875171.79239958.111163.45019978.382165.13499988.426161.1128 9998.47153.4311
10008.53 154.17710018.62158.930710029.15 161.12310039.68161.073810050.21164.0946
10060.74161.189610154.67159.298210175.18161.154210185.44163.8629 10195.7163.9114
10226.18 167.713 10236.3169.872910246.41169.150910296.86171.180610372.82169.6395
#Mann= 3 , 0 , 0
9132.784    0.04       09132.784    0.04       010372.82    0.04       0
#XS Ineff= 2 , 0
       09745.904        10205.37       0
Bank Sta=9132.784,10372.82
Exp/Cntr=0.3,0.1

Type RM Length L Ch R = 1 , 8521.73,145.730200,145.730200,145.730200
XS GIS Cut Line= 6
809988.355752528 809743.74644126810520.337835848809880.682389855
810657.518292099809946.484318331810791.304376304810038.058853179
 810886.05714044810087.108535513811126.817741901810164.197387695
#Sta/Elev= 30
9201.575171.40529259.913170.04489270.213 168.1749290.811168.21279311.409166.0233
9332.007166.38899352.606165.19279445.298165.04559476.195164.1351 9537.99164.4643
9620.383167.93019682.178168.07869705.554169.12549799.707170.14139836.113169.5999
9879.666167.23099947.952160.28129972.578162.24239984.891154.5801   10001 152.583
10009.66153.413310022.11161.637510034.22 163.01510046.18159.275310058.13 157.113
10288.99157.6809 10362.1158.585610392.98164.586210413.52166.640610425.65166.0478
#Mann= 3 , 0 , 0
9201.575    0.04       09201.575    0.04       010425.65    0.04       0
#XS Ineff= 2 , 0
       09821.771        10161.39       0
Bank Sta=9201.575,10425.65
Exp/Cntr=0.3,0.1

Type RM Length L Ch R = 1 ,    8376,118.269800,118.269800,118.269800
XS GIS Cut Line= 6
809961.464666545809766.609608248810375.368063211810006.775776699
 810786.71650067810177.958045706810968.118606627810227.779750884
811060.097139239810239.277067453811178.902743816810208.617556572
#Sta/Elev= 30
9204.071170.14639254.405169.73099300.651167.71789346.897167.34299360.266165.6316
 9370.02163.53619380.191162.65179404.705163.96819459.891162.83599519.667163.9193
9599.368162.6876 9670.62160.61039725.533  159.699801.353159.25669877.172 157.999
9974.654158.10669985.486157.74359990.315156.85019996.317154.877210007.15153.5934
10028.81158.347810050.47157.364410104.63156.683210198.96158.589810268.02159.3183
10363.52162.0065 10466.1163.714510496.65165.020110517.31164.332710531.66164.8643
#Mann= 3 , 0 , 0
9204.071    0.04       09204.071    0.04       010531.66    0.04       0
#XS Ineff= 2 , 0
       09934.846        10159.31       0
Bank Sta=9204.071,10531.66
Exp/Cntr=0.3,0.1

Type RM Length L Ch R = 1 , 8257.73,709.229800,709.229800,709.229800
XS GIS Cut Line= 6
809976.154995754809874.110708557810305.053408302 809996.93367142
810612.784163953810232.703910676810823.599006737810358.100296739
811076.378626169810428.286438003811344.927180683810449.271654096
#Sta/Elev= 30
9258.383168.83779509.968165.0613  9532.1163.09029554.232165.0419 9634.39160.5617
9782.209160.23819808.335159.06629843.505160.33989936.755158.89299952.032160.3157
9968.764156.11989977.062155.36469989.398151.350410001.68149.9216 10025.9155.7089
10111.11155.3985 10133.2160.136810179.41158.259210214.59159.644810289.32160.0417
10320.72159.107610516.43159.2522 10526.5162.368210546.65 161.408 10566.8 162.848
10576.88161.136110597.03160.704710707.29161.524410767.35164.030910777.28163.1745
#Mann= 3 , 0 , 0
9258.383    0.04       09258.383    0.04       010777.28    0.04       0
#XS Ineff= 2 , 0
       0  9919.4        10153.32       0
Bank Sta=9258.383,10777.28
Exp/Cntr=0.3,0.1

Type RM Length L Ch R = 1 ,  7548.5,472.819900,472.819900,472.819900
XS GIS Cut Line= 6
810065.469227909810666.573181111810323.639345635810739.207256657
810452.405923207810803.881481913810517.087529807810821.588688586
810647.270159919810817.517173292810806.897147057810778.182939605
#Sta/Elev= 30
9659.081165.03389668.982165.56259720.923 163.2419731.312163.9546  9741.7161.9959
9762.476161.59359804.029155.85169835.194154.36849897.523153.9144 9911.74151.4044
9928.737151.78449983.699148.27339995.392144.7273   10001144.476810008.22144.8881
10030.51  155.6610052.57154.2494 10075.5157.058110095.45157.694810108.87160.0455
10146.88162.171210177.02163.0677 10227.1161.188610277.71161.208610308.43158.9155
10328.93159.912810339.27161.712610370.26 161.00710407.15162.743210434.22161.5328
#Mann= 3 , 0 , 0
9659.081  0.0456       09659.081  0.0456       010434.22  0.0456       0
#XS Ineff= 2 , 0
       0                               0
Bank Sta=9659.081,10434.22
Exp/Cntr=0.3,0.1

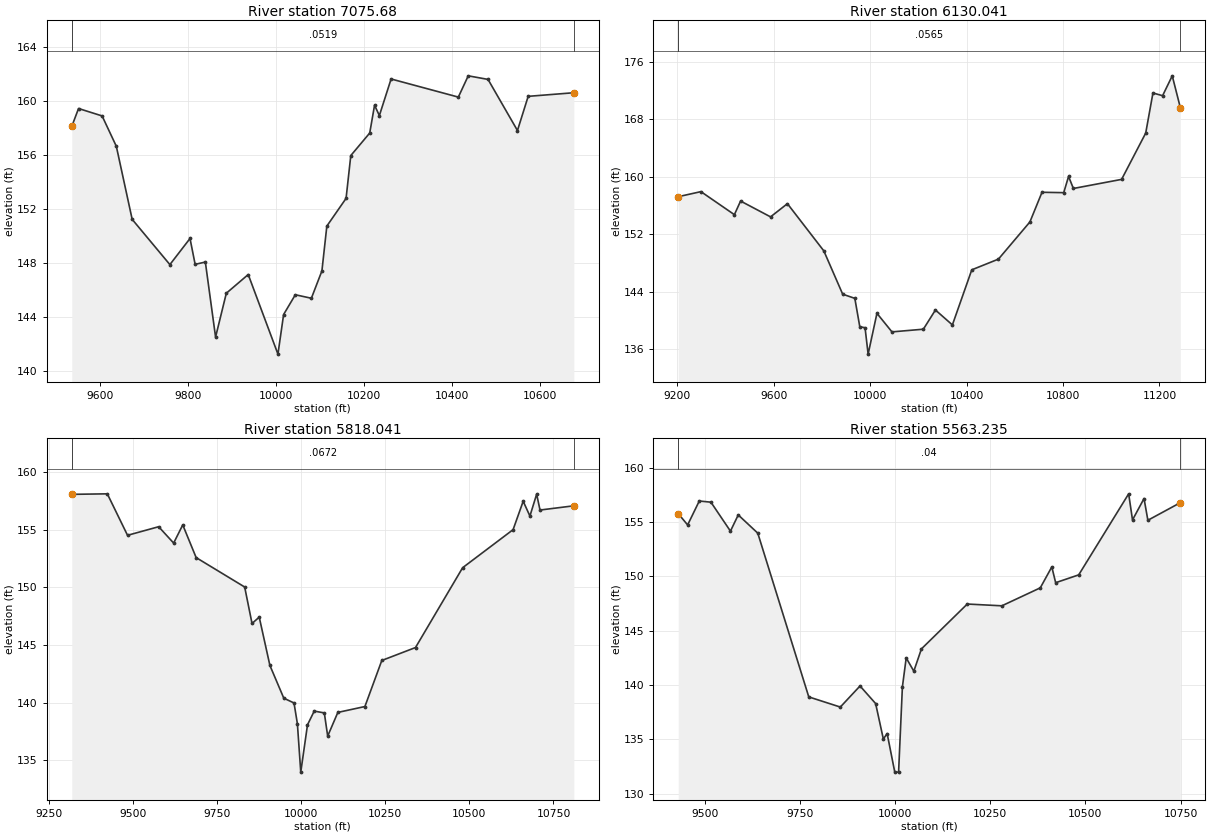
Type RM Length L Ch R = 1 , 7075.68,945.639700,945.639700,945.639700
XS GIS Cut Line= 6
809820.392178945811365.512166625809988.241928096811296.810584163
810117.194077475811225.025588652810169.132084746 811188.17400616
810296.131368938811066.698669494810812.761724014810825.099555265
#Sta/Elev= 30
9536.646158.12539552.023159.45579605.521158.90659637.806 156.6629673.834 151.249
9759.452147.89919805.177149.83289816.789147.92039840.011148.08719863.233 142.533
9887.614145.77879937.384 147.16310004.86141.270810017.75144.204710044.35145.6666
10080.78145.407710104.72147.431910115.91150.7501 10159.6152.802110170.31155.9721
10213.32 157.64110224.26159.6992 10235.2158.932810261.85161.641710414.56160.3002
10437.02161.875310481.96161.610310548.81157.825610573.15160.356510676.86160.6236
#Mann= 3 , 0 , 0
9536.646  0.0519       09536.646  0.0519       010676.86  0.0519       0
#XS Ineff= 2 , 0
       0                               0
Bank Sta=9536.646,10676.86
Exp/Cntr=0.3,0.1

Type RM Length L Ch R = 1 ,6130.041,312.000000,312.000000,312.000000
XS GIS Cut Line= 6
810129.352441162811830.849609002810316.266489863811712.354080737
810663.930838674811417.863143578810933.904502034811477.645125985
811556.304987133811426.364989802812048.428486794811429.044027552
#Sta/Elev= 30
9203.604157.2249 9297.74157.93079436.521154.72379462.279156.61989586.541 154.416
9656.516156.25239807.552 149.6789885.792143.64729936.165143.06639956.721139.1211
9978.608138.97069991.327135.2991 10027.9140.981510090.17138.396710220.44138.7702
10270.54141.444110340.89139.367410421.32147.040510531.92148.532310662.47153.7099
10712.58157.840210802.76157.787610822.78160.046510842.79158.370111042.83 159.637
11142.85166.084811172.85171.671511212.88171.291911252.91174.059511286.37169.6393
#Mann= 3 , 0 , 0
9203.604  0.0565       09203.604  0.0565       011286.37  0.0565       0
#XS Ineff= 2 , 0
       0                10226.97       0
Bank Sta=9203.604,11286.37
Exp/Cntr=0.3,0.1

Type RM Length L Ch R = 1 ,5818.041,254.806100,254.806100,254.806100
XS GIS Cut Line= 6
810185.959201783811944.063130289810336.320180804811887.024520025
810682.512667269811722.814781055810782.530044168811694.671456188
811271.020632982811662.684675917811625.490244452811668.651819961
#Sta/Elev= 30
9318.001 158.0579423.652158.10229483.768154.50669576.289 155.2519620.881153.8331
9647.935 155.409 9687.77152.57459832.019150.02439853.873 146.8649875.289147.4134
9907.016143.22519948.334140.38789978.721139.97189988.752138.1697 9998.77133.9783
10018.78138.079610038.79139.2686 10068.8139.110810078.81137.101510108.98139.1548
10189.42139.663810239.67143.6563 10339.9 144.77910479.97151.697510629.99154.9975
10659.99157.4587   10680156.174310700.01158.072310710.01156.696610810.59 157.065
#Mann= 3 , 0 , 0
9318.001  0.0672       09318.001  0.0672       010810.59  0.0672       0
#XS Ineff= 2 , 0
       0                               0
Bank Sta=9318.001,10810.59
Exp/Cntr=0.3,0.1

Type RM Length L Ch R = 1 ,5563.235,403.925600,403.925600,403.925600
XS GIS Cut Line= 6
810370.790185004812030.658281274810639.386341602811971.937994651
810852.675165325 811914.52977366810890.511104465811907.795424454
811069.336210728811904.633266993 811669.41702643811822.403336994
#Sta/Elev= 30
9430.414155.75929455.106 154.7199485.704156.92119516.303156.81159567.549154.1494
9588.061155.6396 9639.34153.96489773.323 138.905 9856.17137.9715 9907.95139.9102
 9948.93138.29449969.182135.03549979.201135.53239999.236131.987910009.24131.9879
10019.24 139.82410029.24142.491510049.25141.271410069.25143.321210189.68147.4458
10280.52147.281710381.45148.934110411.73150.860410421.82149.407510482.39150.1274
 10613.6157.580310623.69  155.1810653.97157.148510664.07155.149410749.27156.7657
#Mann= 3 , 0 , 0
9430.414    0.04       09430.414    0.04       010749.27    0.04       0
#XS Ineff= 2 , 0
       0                               0
Bank Sta=9430.414,10749.27
Exp/Cntr=0.3,0.1