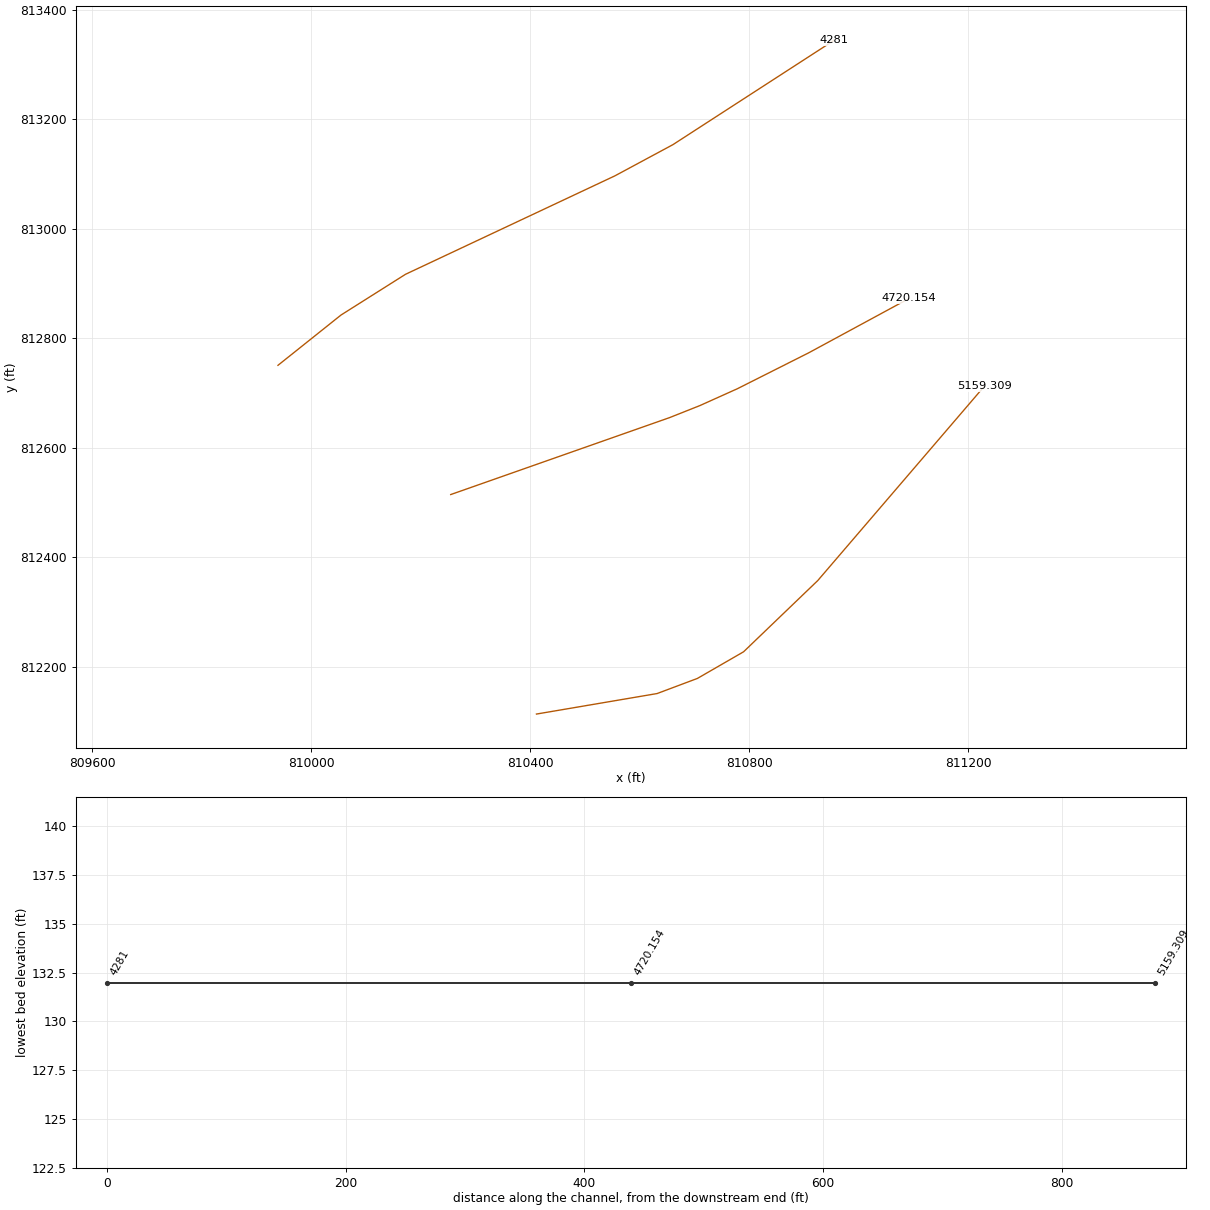
HEC-RAS study 18137_ras.prj: 18137

--- 18137_ras.g01 (geometry) --- (continued)

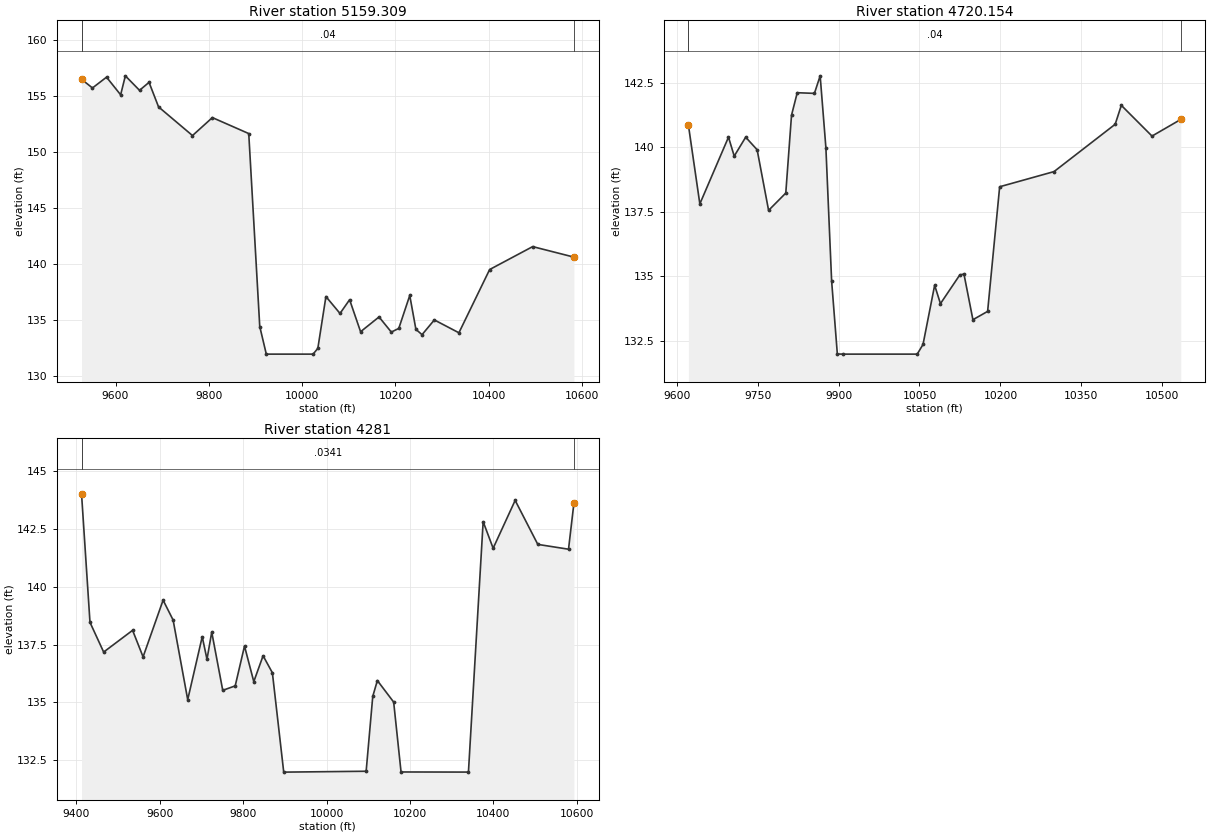
Type RM Length L Ch R = 1 ,5159.309,439.154500,439.154500,439.154500
XS GIS Cut Line= 6
810411.634458334812113.712414641810631.994022402812151.168729949
810705.507216939812178.773367927 810789.76910484812227.370282418
810925.226485316812357.438423611811229.302742571812712.109695449
#Sta/Elev= 30
9527.151156.52019550.571155.74689580.745156.71159610.967155.13459621.042156.8302
9651.444155.53639671.833156.24859692.223 154.057 9764.96151.49799807.574153.1023
9885.525 151.6769909.107134.45289923.139131.987910023.42131.987910033.59132.5024
10050.93137.126710081.11 135.61910101.68136.845610125.21133.987610164.73135.3064
10191.07133.956310207.08134.282710230.59137.225310243.76134.200710256.93133.7248
10283.27135.041110335.96133.893410401.82139.539810494.03141.585410582.43140.6476
#Mann= 3 , 0 , 0
9527.151    0.04       09527.151    0.04       010582.43    0.04       0
#XS Ineff= 2 , 0
       0                               0
Bank Sta=9527.151,10582.43
Exp/Cntr=0.3,0.1

Type RM Length L Ch R = 1 ,4720.154,439.154500,439.154500,439.154500
XS GIS Cut Line= 6
810255.043221611812514.479817124810654.797908558812655.026411935
810710.055529295812676.966309893810778.529048662812707.756804064
810908.486781276812773.173435965811091.907479462812872.488967086
#Sta/Elev= 30
9621.828140.85929643.013137.80669696.093140.39169706.708139.6585 9727.94140.3902
9749.172139.90379770.404 137.5569802.251138.22589812.867141.23999823.483 142.113
 9855.33142.08749865.946142.76719876.562139.98519887.178134.82759897.775131.9925
9908.341131.987910045.79131.987910056.55132.363610078.07134.654910088.83133.9426
10124.62 135.05310132.38135.0892   10149133.320810176.24133.643210198.55138.4704
10299.31139.057810412.61140.890910423.98141.623710480.84140.433310534.18141.0784
#Mann= 3 , 0 , 0
9621.828    0.04       09621.828    0.04       010534.18    0.04       0
#XS Ineff= 2 , 0
       0                               0
Bank Sta=9621.828,10534.18
Exp/Cntr=0.3,0.1

Type RM Length L Ch R = 1 ,    4281,0.000000,0.000000,0.000000
XS GIS Cut Line= 6
809939.644875979812750.474116233810054.848898473 812842.36185719
810172.484244182812916.654576702810554.972140176813096.477813306
810660.777909465813153.386361681810955.534170073813344.206479765
#Sta/Elev= 30
9412.524144.01899432.792138.46289465.571137.17819534.969138.11839560.123136.9699
9608.136139.42239632.143138.56359667.155135.12129701.983137.84059713.376136.8648
 9724.77138.04159751.165135.52379781.064135.71699803.349137.43779825.634   135.9
 9847.92137.01879870.205136.28429897.419131.987910095.09132.025910110.93135.2621
10121.99135.946610161.07135.016410178.77131.9946 10340.4131.989810375.68142.8149
10399.66141.666210452.43143.735810506.76141.832610580.41141.624610593.36143.6183
#Mann= 3 , 0 , 0
9412.524  0.0341       09412.524  0.0341       010593.36  0.0341       0
#XS Ineff= 2 , 0
       0                               0
Bank Sta=9412.524,10593.36
Exp/Cntr=0.3,0.1